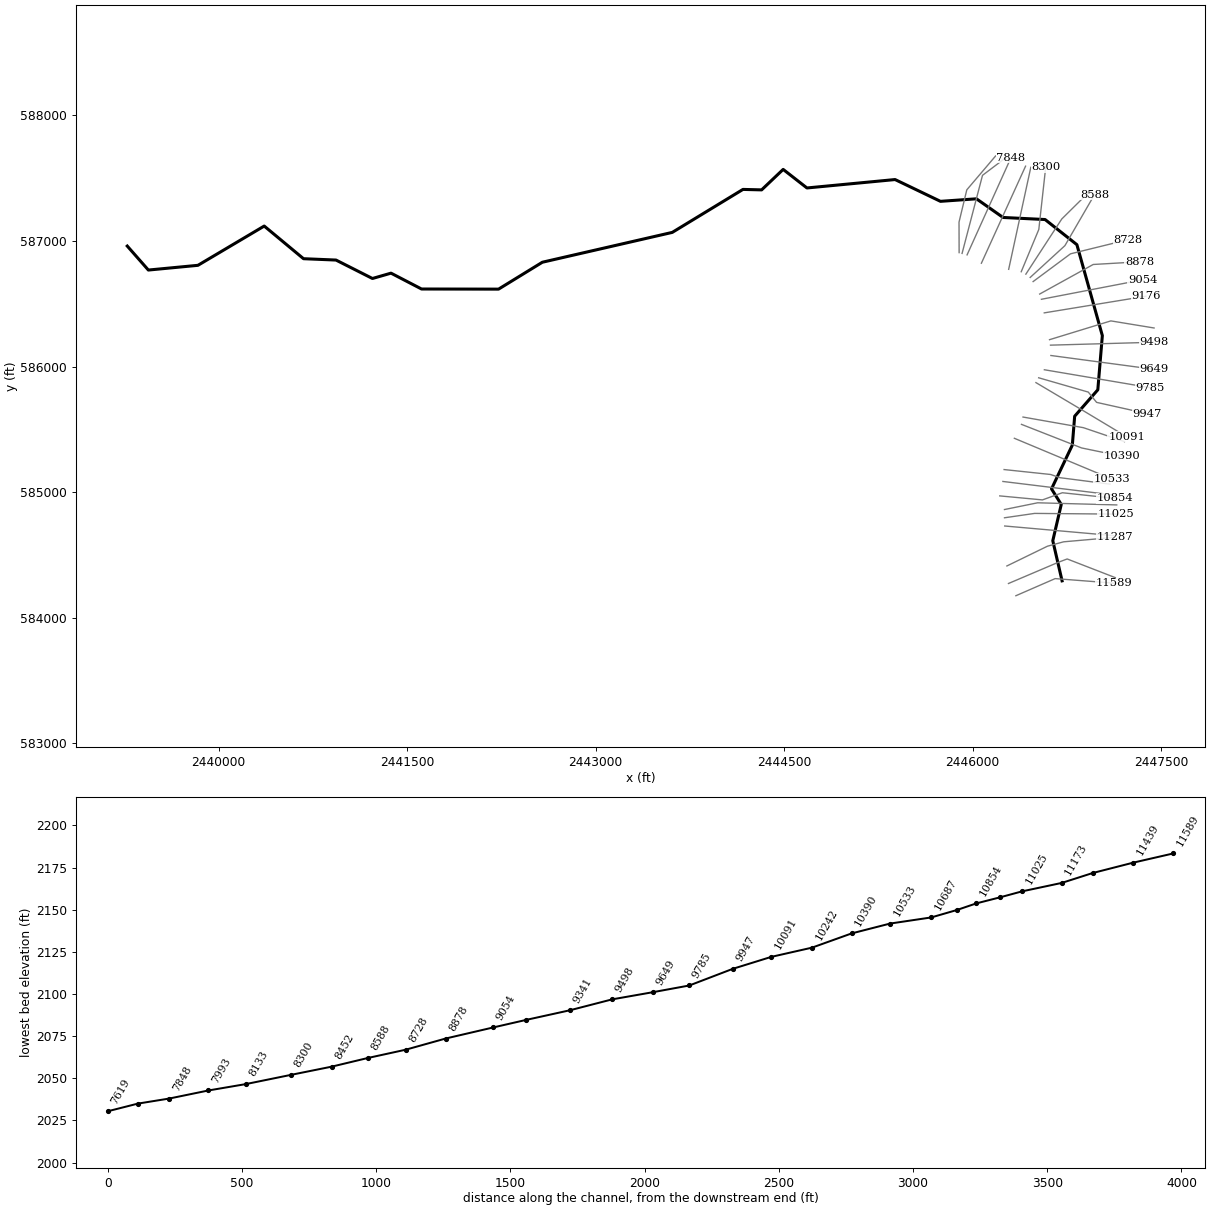
--- DRYRN2.prj (project) ---

Proj Title=DRYRN2
Current Plan=p01
Default Exp/Contr=0,0
English Units
Geom File=g01
Flow File=f01
Plan File=p01
BEGIN DESCRIPTION:
Stream Name: Dry Run (2)
Flood Zone: Approximate
Pendlteon County, West Virginia
HEC-RAS Version: 5.0.7
Hydrology Method:
Regression
END DESCRIPTION:
DSS Export Rating Curves= 0
DSS Export Rating Curve Sorted= 0
DSS Export Volume Flow Curves= 0
DXF OffsetX= 0
DXF OffsetY= 0
DXF ScaleX= 0
DXF ScaleY= 0

--- DRYRN2.p01 (plan) ---

Plan Title=Floodplain
Program Version=4.00
Geom File=g01
Flow File=f01
K Sum by GR=0
Std Step Tol=0.01
Critical Tol=0.01
Num of Std Step Trials=20
Max Error Tol=0.3
Flow Tol Ratio=0.001
Split Flow NTrial=30
Split Flow Tol=0.02
Split Flow Ratio=0.02
Log Output Level=0
Friction Slope Method=1
Unsteady Friction Slope Method=2
Unsteady Bridges Friction Slope Method=1
Global Log Level=0
CheckData=False
Run HTab=0
Run UNet=0
Run PostProcess=0
UNET Theta=0
UNET Theta Warmup=0
UNET ZTol=0
UNET ZSATol=0
UNET MxIter=0
UNET MaxInSteps=0
UNET DtIC=0
UNET DtMin=0
UNET MaxCRTS=0
UNET WFStab=0
UNET SFStab=0
UNET WFX=0
UNET SFX=0
UNET DSS MLevel=0
UNET DZMax Abort=0
UNET Convert EG Bridges=0
UNET Use Existing IB Tables=0
UNET Froude Limit=0
UNET Froude Power=0
Write IC File=0
Echo Input=False
Echo Output=False
Write Detailed=0

--- DRYRN2.f01 (steady flow) ---

Flow Title=Flows
Program Version=5.07
Number of Profiles= 6
Profile Names=P100yr,P10yr,P25yr,P50yr,P500yr,P101yr
River Rch & RM=DRYRN2,Main            ,11589
     553     259     366     457     810     673
River Rch & RM=DRYRN2,Main            ,10687
     865     402     570     713    1273    1052
River Rch & RM=DRYRN2,Main            ,8300
    1007     467     663     830    1485    1226
River Rch & RM=DRYRN2,Main            ,6566
    1150     532     756     947    1698    1399
River Rch & RM=DRYRN2,Main            ,2892
    1281     592     841    1055    1894    1559
Boundary for River Rch & Prof#=DRYRN2,Main            , 1
Up Type= 0
Dn Type= 3
Dn Slope=0.031456
Boundary for River Rch & Prof#=DRYRN2,Main            , 2
Up Type= 0
Dn Type= 3
Dn Slope=0.031456
Boundary for River Rch & Prof#=DRYRN2,Main            , 3
Up Type= 0
Dn Type= 3
Dn Slope=0.031456
Boundary for River Rch & Prof#=DRYRN2,Main            , 4
Up Type= 0
Dn Type= 3
Dn Slope=0.031456
Boundary for River Rch & Prof#=DRYRN2,Main            , 5
Up Type= 0
Dn Type= 3
Dn Slope=0.031456
Boundary for River Rch & Prof#=DRYRN2,Main            , 6
Up Type= 0
Dn Type= 3
Dn Slope=0.031456
DSS Import GetInterval= 0
DSS Import GetPeak= 0
DSS Import FillOption= 0

--- DRYRN2.g01 (geometry) ---

Geom Title=Geometry
Program Version=5.07

River Reach=DRYRN2          ,Main
Reach XY= 30
      2446711.66      584292.873     2446637.833        584612.5
     2446705.154      584901.388     2446627.695      585025.391
     2446793.269      585373.935     2446811.886      585604.004
      2446996.09       585814.58     2447032.185      586246.009
     2446829.533      586970.443     2446576.509      587170.501
     2446241.907      587186.967     2446030.267      587335.586
     2445743.803      587315.455     2445382.568      587488.957
     2444681.304      587421.937     2444491.991      587569.761
     2444320.515      587406.678     2444171.965      587410.399
      2443609.51      587068.092     2442575.604      586830.442
     2442226.949      586616.212     2441613.986      586617.202
     2441371.065      586743.494     2441223.285      586700.952
       2440933.3       586847.76      2440674.72      586858.547
     2440361.951       587118.62     2439834.515      586805.863
     2439440.016      586768.198     2439272.001      586959.248

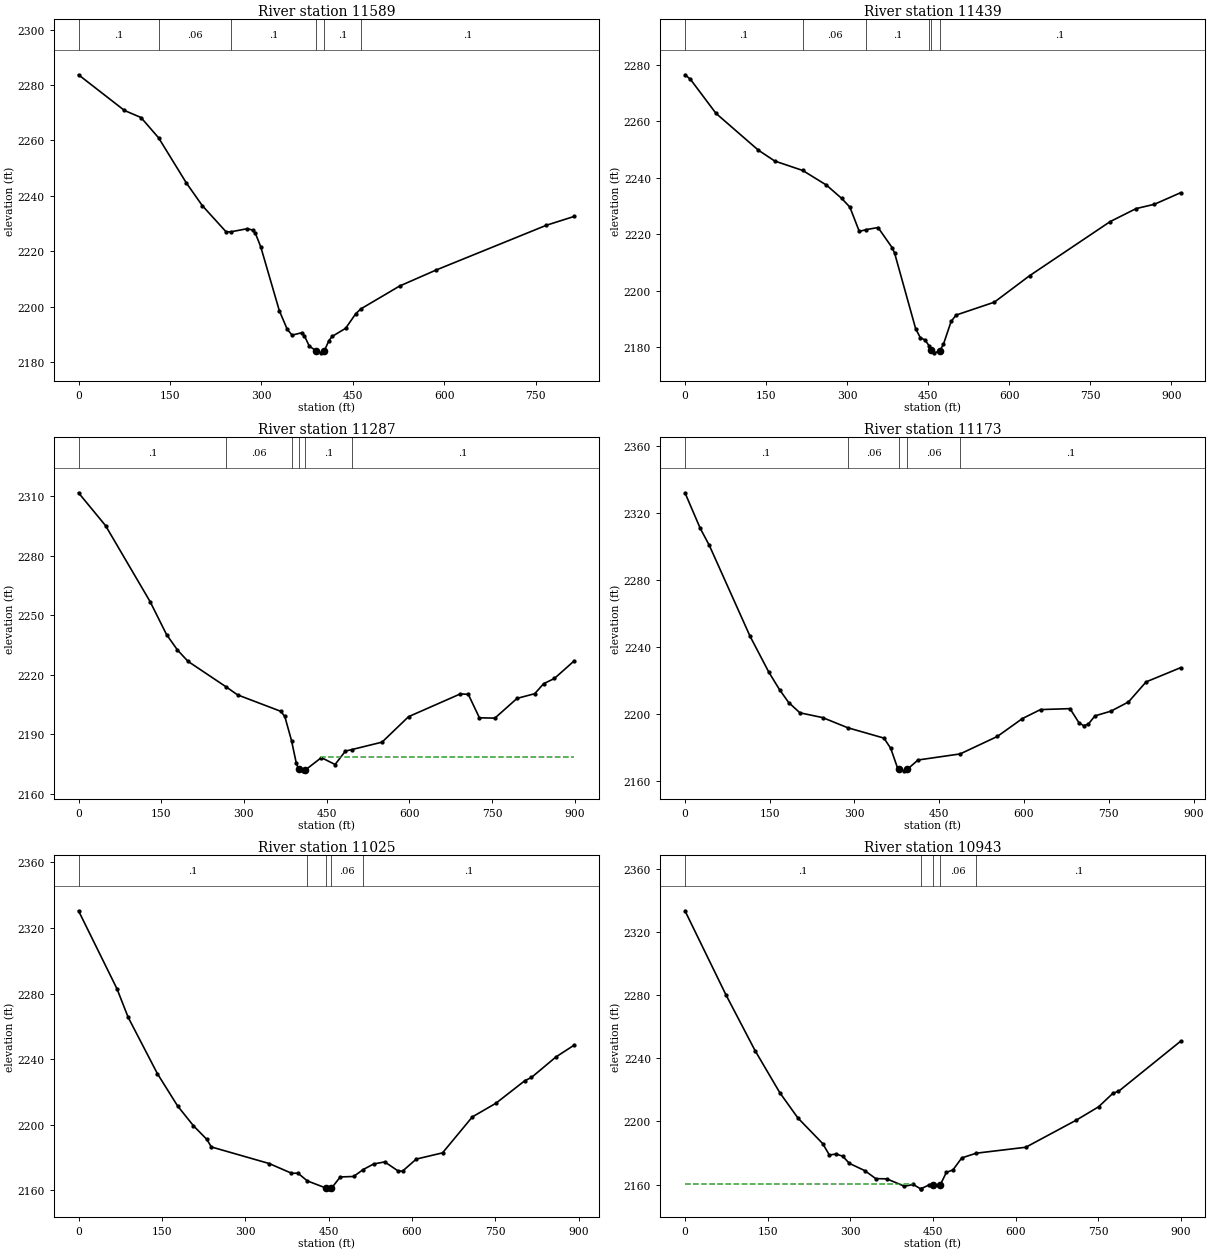
Type RM Length L Ch R = 1 ,11589   ,149.6,149.6,149.6
XS GIS Cut Line= 3
 2446344.0088273584174.3738802172446656.71064178 584310.75276546
     2447127.221      584274.378
#Sta/Elev= 30
       0 2283.69    75.4 2270.81   102.5 2268.27  131.392260.934   176.7 2244.73
     203  2236.5   242.1 2227.02  249.51 2227.01     277 2228.16   285.7 2227.65
   290.1 2226.51   298.8 2221.72   329.4 2198.59   342.4 2191.84   350.4 2189.75
   366.4 2190.62   370.4 2189.56   378.6 2185.77   389.8  2184.1   398.5 2183.36
  403.06 2184.01   410.6 2187.67   415.9 2189.26   438.2 2192.21   454.7 2197.44
  463.162199.215   526.9 2207.48   587.2 2213.29   767.6  2229.4   813.1 2232.58
#Mann= 6 ,-1 , 0
       0      .1       0  131.39     .06       0  249.51      .1       0
   389.8    .045       0  403.06      .1       0  463.16      .1       0
Bank Sta=389.8,403.06
XS Rating Curve= 0 ,0
Exp/Cntr=0.3,0.1

Type RM Length L Ch R = 1 ,11439   ,152.7,151.9,150.4
XS GIS Cut Line= 4
2446285.14259666584271.7919832832446682.05806574 584440.81023454
2446752.22786115584467.1821820722447135.28006184 584318.47327074
#Sta/Elev= 30
       0 2276.51      10 2274.93    57.4 2262.82   135.6  2249.8   166.1 2245.92
  217.842242.574   261.7  2237.4   290.2 2232.63   305.2 2229.56   322.6 2220.95
   335.32221.594   357.3 2222.33   383.4  2215.2   387.9 2213.29   426.9 2186.45
   435.5 2183.27   444.1 2182.46  452.222180.279   456.22178.748   461.2 2177.89
   471.32178.492   478.3 2180.91   492.5 2189.01   501.8 2191.29   572.5 2195.86
   637.6 2205.22     787 2224.45   834.9 2229.05   868.6 2230.57   917.3 2234.68
#Mann= 6 ,-1 , 0
       0      .1       0  217.84     .06       0   335.3      .1       0
  452.22      .1       0   456.2    .045       0   471.3      .1       0
Bank Sta=456.2,471.3
XS Rating Curve= 0 ,0
Exp/Cntr=0.3,0.1

Type RM Length L Ch R = 1 ,11287   ,119.2,114.9,110.5
XS GIS Cut Line= 4
2446272.55274485584411.4637448472446595.14906226584568.741750321
2446724.36352702584603.8475515332447129.09421003584639.302255153
#Sta/Elev= 30
       0 2311.65    49.1  2295.1   129.8  2256.9   159.7 2240.29   179.5 2232.52
   198.6 2226.81  267.962213.929   288.4 2209.95   366.8 2201.67   374.2 2199.05
  386.36 2186.96   394.9 2175.76   399.1 2172.56   407.4  2171.7   411.5 2172.11
   440.5 2178.36   465.4 2174.89   484.1 2181.63  495.272182.366   550.6 2186.14
   598.7 2198.96   692.7 2210.43   707.1 2210.18   727.2 2198.39   755.3 2198.23
   795.5 2208.17   827.6 2210.53   843.6 2215.54   863.2 2218.18   899.1 2227.04
#Mann= 6 ,-1 , 0
       0      .1       0  267.96     .06       0  386.36      .1       0
   399.1    .045       0   411.5      .1       0  495.27      .1       0
#XS Ineff= 2 , 0
                          440.65         2178.58
Permanent Ineff=
       F       F
Bank Sta=399.1,411.5
XS Rating Curve= 0 ,0
Exp/Cntr=0.3,0.1

Type RM Length L Ch R = 1 ,11173   ,146.7,148,146.8
XS GIS Cut Line= 2
 2446255.1065118584729.7547502372447128.90121003584652.436448467
#Sta/Elev= 30
       0 2332.16      27 2310.89      43 2300.75   115.2 2246.32   148.4 2224.86
   167.5 2214.32   183.5 2206.72   203.4 2200.56   243.8 2197.68  287.882191.652
   352.2 2185.42   364.2 2179.25   376.3 2167.45   379.32166.752   388.2 2165.85
   393.82166.847   412.4 2172.33  487.04 2175.97   552.9 2186.43   597.1 2197.11
   629.2 2202.49   681.4 2203.05   697.5 2194.48   705.5 2192.92   713.6 2193.69
   725.6 2198.73   753.7 2201.53   784.9 2207.05   816.1 2219.05   877.2 2227.56
#Mann= 5 ,-1 , 0
       0      .1       0  287.88     .06       0   379.3    .045       0
   393.8     .06       0  487.04      .1       0
Bank Sta=379.3,393.8
XS Rating Curve= 0 ,0
Exp/Cntr=0.3,0.1

Type RM Length L Ch R = 1 ,11025   ,81.9,81.5,81.5
XS GIS Cut Line= 3
2446253.44206189 584795.200495382446493.44743349584830.013794127
2447142.67268383584824.418804913
#Sta/Elev= 30
       0  2330.5    69.2 2282.91    89.4 2265.45   141.9 2231.13   178.3  2211.4
   206.6 2199.41   230.9    2191     239  2186.4     343 2176.29     383  2170.4
     395 2170.35  411.692165.682   444.42161.427     451 2160.84     455 2161.18
     471  2168.1     495 2168.38  512.17  2172.6     531 2176.01     551 2177.28
     575 2171.75     583 2171.64   607.7    2179     655  2182.8   708.6 2204.74
     751 2213.06     803 2226.82     815 2228.81     859 2241.31   891.8 2248.53
#Mann= 5 ,-1 , 0
       0      .1       0  411.69     .06       0   444.4    .045       0
     455     .06       0  512.17      .1       0
Bank Sta=444.4,455
XS Rating Curve= 0 ,0
Exp/Cntr(USF)=0,0
Exp/Cntr=0.3,0.1

Type RM Length L Ch R = 1 ,10943   ,83.1,88.7,92.7
XS GIS Cut Line= 3
2446253.26506342584860.8565829862446517.38159468584914.531300811
2447146.75410276584897.602868479
#Sta/Elev= 30
       0 2333.26    74.2 2280.16   127.2 2244.75   172.1 2218.11   204.8 2202.17
   249.7 2185.99   261.9 2178.75   274.1 2179.34   286.1 2177.99   298.1 2173.44
   326.1 2168.85   346.1 2163.78   366.1 2163.64   398.1 2158.94   414.1 2160.08
   427.4 2157.32  428.062157.355   442.1 2159.69   450.1 2159.49  462.66 2159.49
   474.1 2167.71   486.1  2169.3   502.1 2176.89  528.272179.869   618.2 2183.63
   710.2 2200.86   750.2 2209.22   776.9 2217.97   786.2 2218.93   899.1 2250.73
#Mann= 5 ,-1 , 0
       0      .1       0  428.06     .06       0   450.1    .045       0
  462.66     .06       0  528.27      .1       0
#XS Ineff= 2 , 0
          411.32 2160.55
Permanent Ineff=
       F       F
Bank Sta=450.1,462.66
XS Rating Curve= 0 ,0
Exp/Cntr(USF)=0,0
Exp/Cntr=0.3,0.1

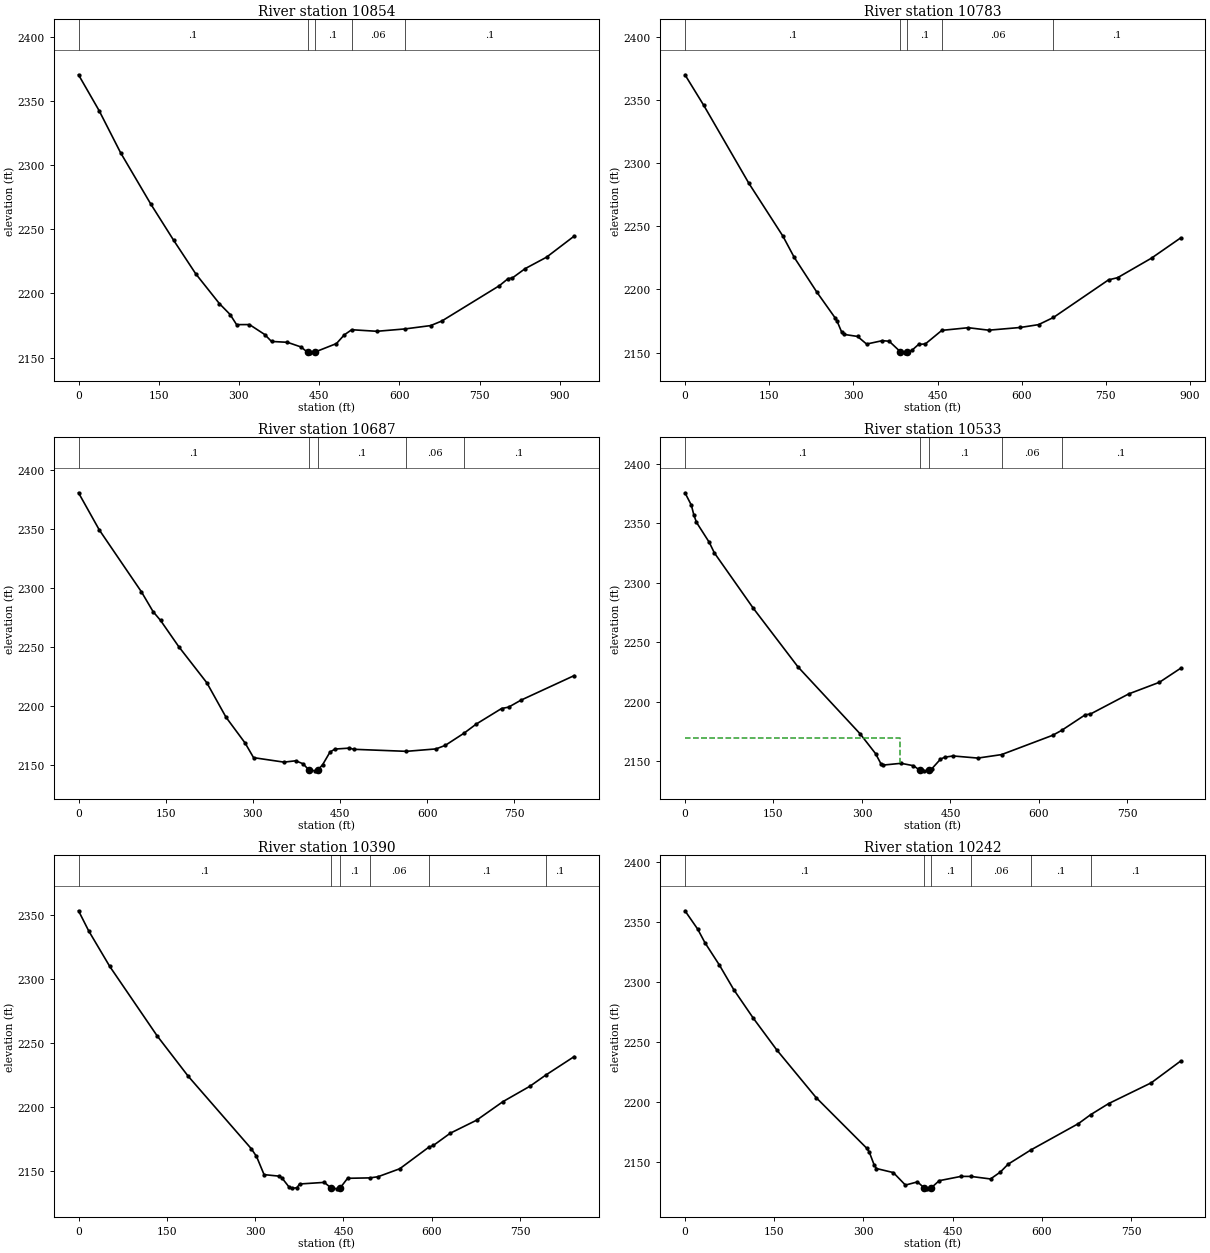
Type RM Length L Ch R = 1 ,10854   ,77.3,71.8,65.9
XS GIS Cut Line= 4
2446215.66855985584969.4827198312446555.38335338 584937.56320903
2446713.84092486584994.5623354612447128.79456528584950.103016845
#Sta/Elev= 30
       0 2370.62    38.5 2342.68    78.6 2309.88   134.9 2269.94   177.8 2241.59
   219.2 2215.37   263.4 2192.15   283.5 2183.61   295.6 2175.72   319.7 2175.76
   348.2 2168.01   360.9  2162.6   390.7 2161.93   416.2 2158.27   428.3 2154.15
   433.2 2153.71   441.7 2154.25   482.4 2160.95   496.9 2167.69   510.9 2171.74
   557.9 2170.52   610.4 2172.36   658.5 2174.97   679.5 2178.55   787.2 2206.14
   803.3  2211.6   811.4 2212.14   835.2 2219.39   875.2 2228.32   926.9 2244.76
#Mann= 5 ,-1 , 0
       0      .1       0   428.3    .045       0   441.7      .1       0
   510.9     .06       0   610.4      .1       0
Bank Sta=428.3,441.7
XS Rating Curve= 0 ,0
Exp/Cntr(USF)=0,0
Exp/Cntr=0.3,0.1

Type RM Length L Ch R = 1 ,10783   ,98.6,96,93.1
XS GIS Cut Line= 2
2446240.74895183 585084.436875672447117.44065524584977.039358374
#Sta/Elev= 30
       0 2369.81    33.5 2345.59     114 2283.84   174.5 2242.15   194.6  2225.4
   234.9 2197.91   267.2 2177.68   271.1 2174.82   279.3 2166.13   283.3 2164.42
   307.5  2162.8   323.6 2156.77   351.8 2159.46   363.9 2158.99     384 2150.59
   392.1 2149.82   396.1 2150.23   404.2 2151.76   416.3  2156.5   428.3 2156.86
  457.732167.605   504.9  2169.7   541.2 2167.74   597.4 2169.88     630 2172.13
  656.512177.791   754.7 2207.55   770.9 2209.28   831.3 2224.75   883.2 2240.74
#Mann= 5 ,-1 , 0
       0      .1       0     384    .045       0   396.1      .1       0
  457.73     .06       0  656.51      .1       0
Bank Sta=384,396.1
XS Rating Curve= 0 ,0
Exp/Cntr=0.3,0.1

Type RM Length L Ch R = 1 ,10687   ,153.9,153.5,152.5
XS GIS Cut Line= 4
     2446250.311      585179.2262446620.97319331 585139.97253092
2446695.35450293585114.455163717      2447093.77      585062.892
#Sta/Elev= 30
       0 2380.91    35.8 2349.42   108.2 2297.08   128.4 2280.22   141.2 2272.79
   172.6 2250.53   220.9 2219.95   253.9 2190.78   286.7 2168.97   301.3 2156.56
   353.6 2152.76   373.8  2153.9   386.4 2151.39   396.42146.202   407.6 2145.39
   412.12146.201   420.2 2150.63   432.9 2161.33   441.4 2163.84     466 2164.63
   474.1 2163.63  564.19 2161.91   615.3 2163.96   631.2 2166.95  663.562177.288
   684.7 2185.05   728.2 2198.19   740.3 2199.36   761.4 2205.22   853.1 2226.05
#Mann= 5 ,-1 , 0
       0      .1       0   396.4    .045       0   412.1      .1       0
  564.19     .06       0  663.56      .1       0
Bank Sta=396.4,412.1
XS Rating Curve= 0 ,0
Exp/Cntr=0.3,0.1

Type RM Length L Ch R = 1 ,10533   ,142.7,143.2,143.3
XS GIS Cut Line= 2
     2446331.979      585428.253     2447106.934      585103.922
#Sta/Elev= 30
       0 2375.79    10.8 2365.36    15.1 2357.03    19.5 2350.91    41.2 2334.04
    49.8  2325.2   115.7 2278.66   191.5 2229.26     297 2172.82     323 2156.26
   332.1 2147.74     336  2146.6   366.3 2148.09   387.2 2146.07   398.12142.232
   405.4 2141.75   413.1 2142.06   418.4 2143.52     433 2151.52     440 2153.22
   454.4 2154.27   496.4 2152.49   536.52155.408   623.4 2171.71  638.642175.874
   678.5 2188.95   687.2 2189.55   752.2 2206.52   804.2  2216.3   840.1 2228.08
#Mann= 5 ,-1 , 0
       0      .1       0   398.1    .045       0   413.1      .1       0
   536.5     .06       0  638.64      .1       0
#XS Ineff= 2 , 0
           364.9 2169.79
Permanent Ineff=
       F       F
Bank Sta=398.1,413.1
XS Rating Curve= 0 ,0
Exp/Cntr=0.3,0.1

Type RM Length L Ch R = 1 ,10390   ,144.7,147.7,150.1
XS GIS Cut Line= 3
     2446388.488      585539.2172446867.34588914585351.268576043
     2447188.061      585285.167
#Sta/Elev= 30
       0 2353.44    17.3 2337.71    53.1 2309.88   133.5 2255.63   186.3 2224.02
   293.2 2167.45   302.3 2161.31   315.2 2147.02     341 2145.83   345.3 2144.59
   358.2 2136.98   362.5 2136.26   371.1 2136.82   375.4  2139.7   417.4 2140.96
   428.62136.766   439.8 2135.91     4442136.366     457 2144.15  494.87 2144.48
   508.6 2145.37   545.6 2151.62   594.72168.398   602.8 2169.88   631.4 2179.42
   676.3 2189.65   721.2 2204.21   766.9 2216.22  793.51 2224.86   841.9 2239.36
#Mann= 6 ,-1 , 0
       0      .1       0   428.6    .045       0     444      .1       0
  494.87     .06       0   594.7      .1       0  793.51      .1       0
Bank Sta=428.6,444
XS Rating Curve= 0 ,0
Exp/Cntr=0.3,0.1

Type RM Length L Ch R = 1 ,10242   ,155.6,151.6,147.2
XS GIS Cut Line= 3
     2446400.836      585597.4412446881.13652702585512.819724233
     2447208.579      585401.733
#Sta/Elev= 30
       0 2359.11    21.4 2343.82    33.6 2332.49    57.8 2313.95      82 2293.43
   114.8  2269.7   154.5  2243.1   220.4 2203.56   305.7 2161.28   309.8 2158.26
   317.9 2147.69     322 2144.39   350.4 2141.01   370.7  2130.6     391 2133.26
  401.83 2128.42   407.2 2127.47   414.3 2128.39   427.5 2134.26   464.1 2137.84
  480.832137.811   513.8  2135.7   530.3 2141.44   543.4 2148.01  581.452159.812
   661.7 2181.84  682.15 2189.24   712.3 2198.46   784.1  2215.8   833.5 2233.92
#Mann= 6 ,-1 , 0
       0      .1       0  401.83    .045       0   414.3      .1       0
  480.83     .06       0  581.45      .1       0  682.15      .1       0
Bank Sta=401.83,414.3
XS Rating Curve= 0 ,0
Exp/Cntr=0.3,0.1

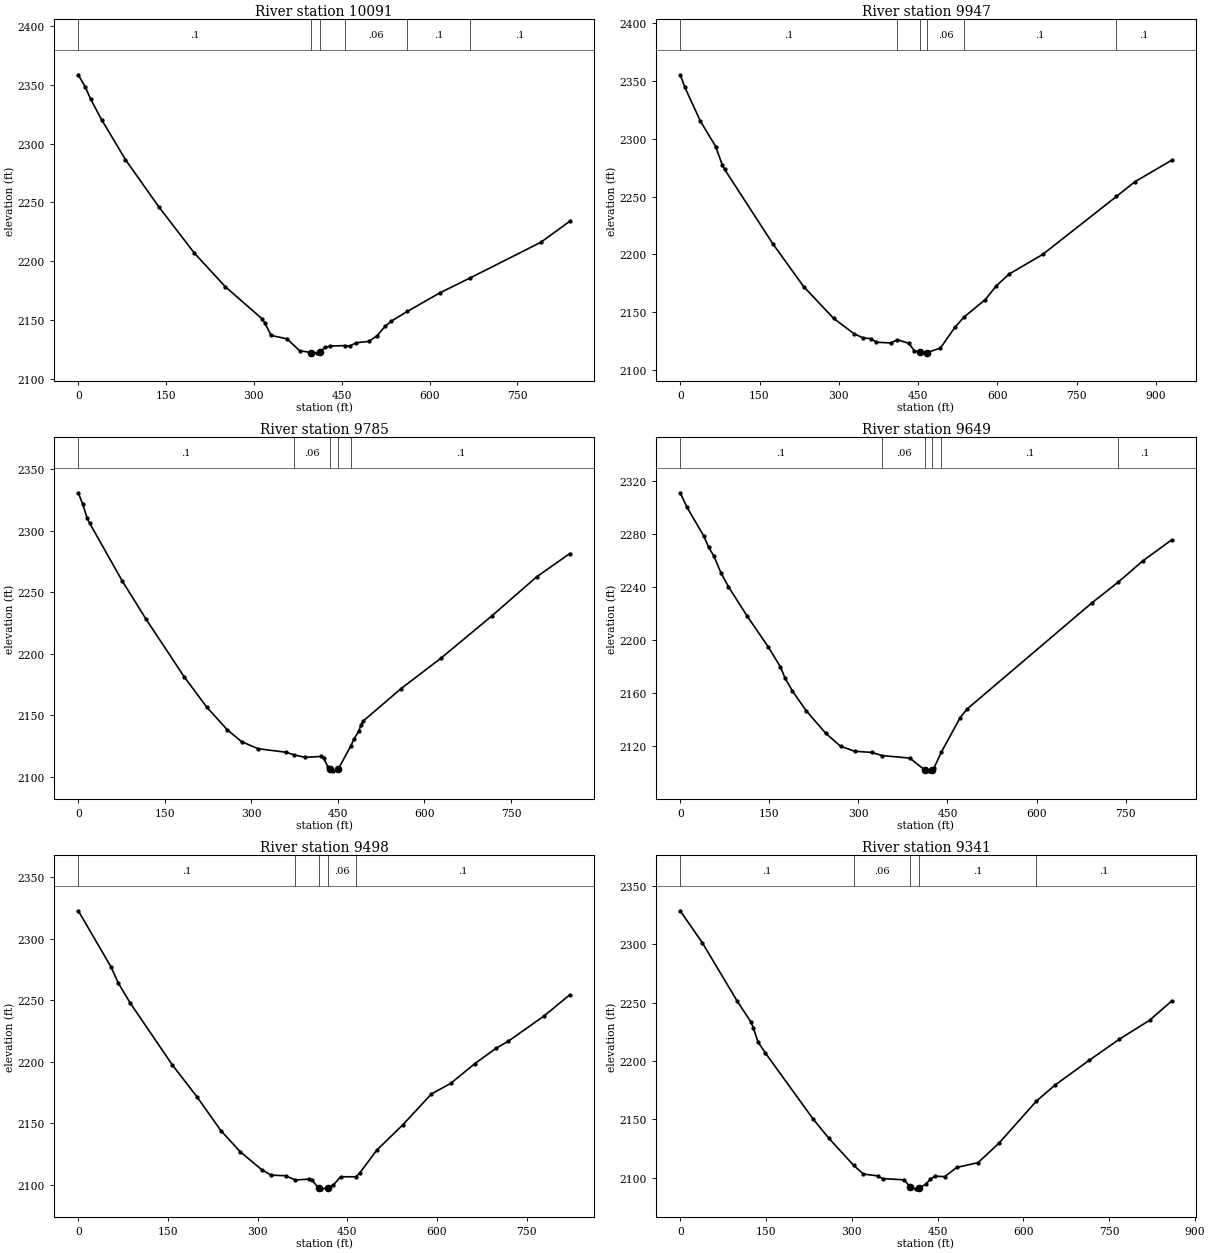
Type RM Length L Ch R = 1 ,10091   ,147.2,143.1,139.2
XS GIS Cut Line= 3
       2446503.6      585871.723 2446892.7348273585640.578958773
     2447224.467      585441.329
#Sta/Elev= 30
       0 2358.61      12 2348.11    21.3 2337.64    39.9 2320.37    80.6 2286.39
   137.6 2246.19   198.1 2206.99     251 2178.34   313.7 2151.06     319 2147.19
   329.3  2136.8   356.3 2133.96   378.3 2123.74   398.1 2122.26   407.5    2122
   412.1 2122.73   421.4 2126.59   430.7 2127.78  454.912128.146   463.3 2127.71
   474.6 2130.55   495.9 2131.71   509.9 2136.28   523.9 2144.42   534.7 2148.97
  561.862157.198   617.4 2172.98  668.812185.602   789.9 2216.02   839.6 2233.93
#Mann= 6 ,-1 , 0
       0      .1       0   398.1    .045       0   412.1      .1       0
  454.91     .06       0  561.86      .1       0  668.81      .1       0
Bank Sta=398.1,412.1
XS Rating Curve= 0 ,0
Exp/Cntr=0.3,0.1

Type RM Length L Ch R = 1 ,9947    ,154.3,162.4,170.6
XS GIS Cut Line= 4
2446525.42936601585910.1469420572446920.31168301 585796.15044457
2446986.49193191 585714.333680182447389.95126797585624.377033433
#Sta/Elev= 30
       0 2355.32     8.8 2344.54      38 2315.39    67.1 2293.26    79.6 2277.32
    83.8  2273.7   175.4 2209.08   233.6 2172.15     290 2144.81   328.8 2131.46
     346 2127.81   361.1 2127.17     371 2124.11   398.8 2123.44  410.822126.295
   432.4 2123.13   442.7 2116.82   453.62115.477   463.3 2114.93     4672115.172
   492.2 2119.08   519.7  2137.1  536.982145.918   577.1    2161   597.6 2172.73
   622.5 2183.14   685.8 2200.07  825.152250.132   859.8 2262.79   929.6 2281.47
#Mann= 6 ,-1 , 0
       0      .1       0  410.82     .06       0   453.6    .045       0
     467     .06       0  536.98      .1       0  825.15      .1       0
Bank Sta=453.6,467
XS Rating Curve= 0 ,0
Exp/Cntr=0.3,0.1

Type RM Length L Ch R = 1 ,9785    ,135.7,136.2,136.2
XS GIS Cut Line= 2
2446570.67804512585974.121366013     2447410.683      585831.882
#Sta/Elev= 30
       0 2330.95     7.4 2322.02    15.5  2310.2    19.5 2306.38    76.3  2259.2
   116.9 2228.65   183.3 2181.61   222.3 2157.01   258.3 2138.32   283.2 2128.71
   311.6 2123.01   360.3 2120.12  373.442118.079   392.7 2116.03   421.1 2116.69
   425.2 2115.32   433.3 2107.77   435.82106.613   442.2 2105.03   450.62106.508
  472.752125.545   477.9 2130.95     486 2137.03   490.1 2142.66   494.1 2145.59
     559 2171.65     628 2196.32   717.2 2231.04   794.3 2262.58     852  2281.6
#Mann= 5 ,-1 , 0
       0      .1       0  373.44     .06       0   435.8    .045       0
   450.6     .06       0  472.75      .1       0
Bank Sta=435.8,450.6
XS Rating Curve= 0 ,0
Exp/Cntr=0.3,0.1

Type RM Length L Ch R = 1 ,9649    ,148.8,151,152.2
XS GIS Cut Line= 2
     2446622.663      586087.666     2447442.859      585977.777
#Sta/Elev= 30
       0 2310.78    11.4 2299.89    39.6 2278.24    47.7 2269.86    56.4 2263.26
    68.8 2250.25    81.3 2239.91   112.2  2218.1   148.6 2194.33   168.7 2179.45
   176.8 2170.77   188.9 2161.28   212.1 2146.38     245 2129.36   269.9 2119.62
   293.8 2115.82   322.1 2114.94  340.412112.521   386.6 2110.65   412.22101.485
   418.9 2101.04  423.72 2101.42     427 2102.95  439.772115.204   471.4 2141.24
   483.5 2147.83   693.3 2227.82  737.832243.509   778.8  2259.4   827.5 2275.24
#Mann= 6 ,-1 , 0
       0      .1       0  340.41     .06       0   412.2    .045       0
  423.72     .06       0  439.77      .1       0  737.83      .1       0
Bank Sta=412.2,423.72
XS Rating Curve= 0 ,0
Exp/Cntr=0.3,0.1

Type RM Length L Ch R = 1 ,9498    ,153.8,157.2,160.5
XS GIS Cut Line= 2
     2446619.403       586170.05     2447441.169       586193.12
#Sta/Elev= 30
       0 2322.61    54.5 2277.19      67 2263.87    86.5 2247.95   157.5 2197.31
   198.6 2171.46   238.6 2144.02   270.6 2127.05   306.6 2112.39   322.6 2107.93
   346.6 2107.45  363.142103.974   386.6 2104.73   390.6    2104   402.4 2097.27
   406.6 2096.81   417.42097.722   426.6 2099.79   438.6 2106.62  464.262106.594
   470.7 2109.65   499.2 2128.24   542.7 2148.73   590.7 2173.89   622.7 2182.39
   662.7 2198.27   698.7 2210.96   718.7 2216.51   779.2 2237.25   822.1 2254.41
#Mann= 5 ,-1 , 0
       0      .1       0  363.14     .06       0   402.4    .045       0
   417.4     .06       0  464.26      .1       0
Bank Sta=402.4,417.4
XS Rating Curve= 0 ,0
Exp/Cntr=0.3,0.1

Type RM Length L Ch R = 1 ,9341    ,165.7,164.1,162.3
XS GIS Cut Line= 3
     2446611.831      586213.6312447099.93773111586363.261706641
2447443.85417208586306.746138959
#Sta/Elev= 30
       0  2328.7    38.4 2301.49    99.2 2251.67   123.5 2233.45   127.7 2228.63
   136.1 2216.18   148.6 2207.01   232.3 2150.22   259.3 2133.96  303.092110.542
   320.1 2103.03   345.2 2101.47   353.6 2099.15   391.2 2098.07   402.5 2091.82
   412.1 2090.35   417.42091.253   428.9 2094.08   437.2 2098.65   445.6 2101.22
   462.3 2100.81   483.4 2108.69   520.6 2112.81   557.1 2129.46  622.432165.461
   654.3 2178.99   715.1  2200.6   767.8 2218.69   820.5 2234.85   859.1 2251.39
#Mann= 5 ,-1 , 0
       0      .1       0  303.09     .06       0   402.5    .045       0
   417.4      .1       0  622.43      .1       0
Bank Sta=402.5,417.4
XS Rating Curve= 0 ,0
Exp/Cntr=0.3,0.1

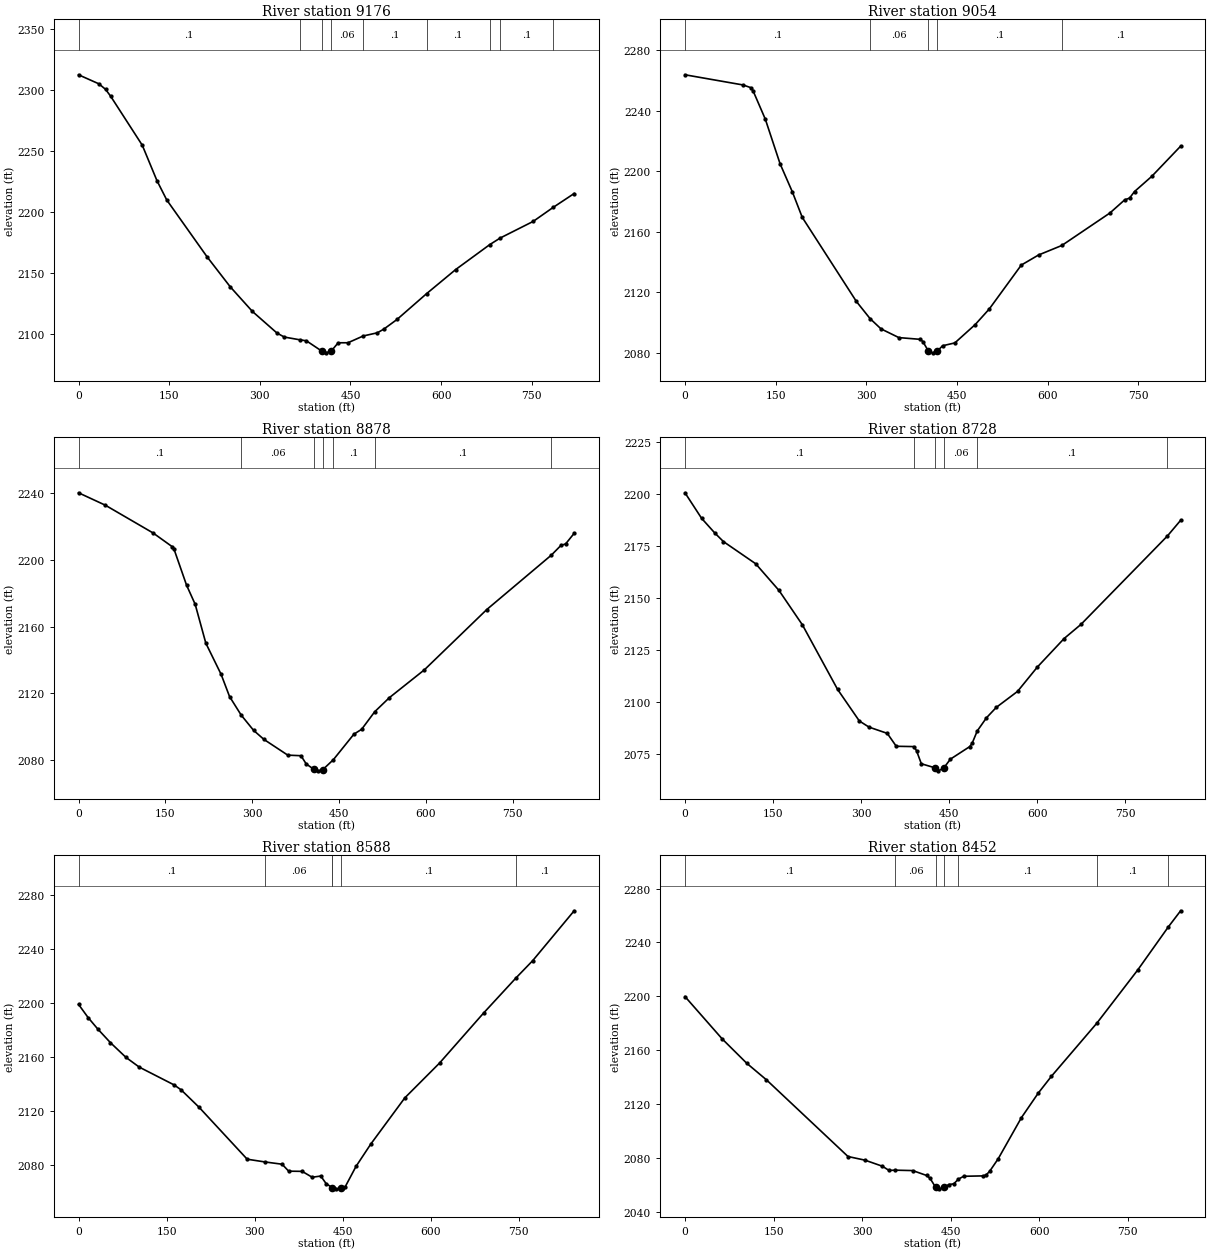
Type RM Length L Ch R = 1 ,9176    ,121.8,122.2,122.5
XS GIS Cut Line= 2
     2446569.852      586427.178      2447379.29      586559.782
#Sta/Elev= 30
       0 2312.15    33.7 2304.75    44.7 2300.26    53.1 2294.65   105.5 2254.51
   129.8 2225.52     146 2209.71   212.7 2163.19     251 2138.68   287.8 2118.46
   328.4 2100.81   340.5 2097.52   366.4 2095.25     377 2094.47   403.32085.779
   409.4  2084.6   418.32086.117   429.7 2092.83   445.9 2092.85  471.14  2098.4
   494.5    2101   505.3 2104.04     527 2111.89  575.882132.986   624.2 2152.79
  680.612173.196  697.792178.554   752.5 2192.19  785.352203.587   820.2 2214.99
#Mann= 9 ,-1 , 0
       0      .1       0   366.4     .06       0   403.3    .045       0
   418.3     .06       0  471.14      .1       0  575.88      .1       0
  680.61      .1       0  697.79      .1       0  785.35      .1       0
Bank Sta=403.3,418.3
XS Rating Curve= 0 ,0
Exp/Cntr=0.3,0.1

Type RM Length L Ch R = 1 ,9054    ,172.8,176.8,180.6
XS GIS Cut Line= 2
     2446547.328        586535.4      2447352.76      586690.644
#Sta/Elev= 30
       0 2263.79    96.3 2257.05   108.6 2255.33   112.6 2253.29     133 2234.43
   157.4    2205   177.8 2186.36   194.1  2169.6   283.7 2114.06  306.372102.721
   324.4 2095.97     354  2090.2   389.6 2089.05   393.7 2087.57   402.92081.262
     410 2080.14   417.92081.404   426.3 2084.81   446.6 2086.69   480.4 2098.84
   503.7 2109.15   556.6 2138.11   585.1 2144.75  623.692151.055   703.2 2172.48
   727.7 2181.17   735.8 2182.35     744 2186.68   772.5 2196.69   820.3 2216.64
#Mann= 5 ,-1 , 0
       0      .1       0  306.37     .06       0   402.9    .045       0
   417.9      .1       0  623.69      .1       0
Bank Sta=402.9,417.9
XS Rating Curve= 0 ,0
Exp/Cntr=0.3,0.1

Type RM Length L Ch R = 1 ,8878    ,152.9,149.8,146.4
XS GIS Cut Line= 3
     2446533.445      586577.1032446959.40938038586812.531144855
2447328.60463399586834.003114757
#Sta/Elev= 30
       0 2240.13    46.3  2232.7   128.9 2216.05   161.9 2207.85   165.1  2206.3
   186.7  2184.8   201.6 2173.34     220 2150.05   246.4  2131.4     261 2118.08
  281.112106.968   302.5 2097.85   320.4 2092.41   361.6 2082.99   384.4 2082.65
   393.5 2077.72   407.12074.395   414.1 2073.59   422.12074.313  440.392080.267
   475.9 2095.56   489.2 2098.45  511.882109.004   537.2 2117.43   597.8 2134.13
   705.5  2170.2  817.112202.801   833.7 2208.62   841.7 2209.49   856.5 2215.86
#Mann= 7 ,-1 , 0
       0      .1       0  281.11     .06       0   407.1    .045       0
   422.1     .06       0  440.39      .1       0  511.88      .1       0
  817.11      .1       0
Bank Sta=407.1,422.1
XS Rating Curve= 0 ,0
Exp/Cntr=0.3,0.1

Type RM Length L Ch R = 1 ,8728    ,130.5,140,149.9
XS GIS Cut Line= 3
     2446481.317      586676.4262446778.80213147       586897.44
     2447238.751      587010.692
#Sta/Elev= 30
       0 2200.48    28.3 2188.22    50.6 2181.22    65.5 2177.04   120.4  2166.4
   160.2 2153.55   200.1    2137   259.9 2106.06     297 2090.87   313.5 2087.92
   344.6 2084.92   359.9 2078.72  389.962078.563   394.4 2076.62   402.6 2070.32
   426.32068.337   431.5 2066.92   440.72068.247   452.1 2072.53     485 2078.55
   489.1 2080.11  497.892086.102   513.6 2092.41   530.3  2097.4   566.5 2105.08
   600.3 2116.79   645.8 2130.46   674.5 2137.25  821.672179.697   844.3 2187.25
#Mann= 6 ,-1 , 0
       0      .1       0  389.96     .06       0   426.3    .045       0
   440.7     .06       0  497.89      .1       0  821.67      .1       0
Bank Sta=426.3,440.7
XS Rating Curve= 0 ,0
Exp/Cntr=0.3,0.1

Type RM Length L Ch R = 1 ,8588    ,135.8,135.3,134.7
XS GIS Cut Line= 3
     2446457.849      586709.2092446734.32822631 586962.66160191
     2446969.868      587369.083
#Sta/Elev= 30
       0 2198.74    16.4 2188.92    32.7 2180.52    54.4 2170.35    80.9 2159.43
   103.5 2152.24     163 2139.03   174.9 2135.39   205.5 2122.48   287.5    2084
  317.922081.962     347 2080.29   358.2 2075.14   381.2    2075   398.2 2070.64
   412.9 2071.53   422.1 2065.88  431.84 2063.11   432.32062.995   439.7 2062.05
   446.82062.355   454.5 2063.53     473 2078.69   498.2 2095.25   556.2 2129.47
   615.3 2155.21   690.3 2192.24   745.82218.383   774.1  2231.1   844.8 2268.06
#Mann= 6 ,-1 , 0
       0      .1       0  317.92     .06       0  431.84      .1       0
   432.3    .045       0   446.8      .1       0   745.8      .1       0
Bank Sta=432.3,446.8
XS Rating Curve= 0 ,0
Exp/Cntr=0.3,0.1

Type RM Length L Ch R = 1 ,8452    ,146.3,152.1,157.8
XS GIS Cut Line= 3
     2446423.576      586735.6452446709.21192297587174.829022494
     2446933.761      587396.932
#Sta/Elev= 30
       0 2199.81      63 2168.34   104.7 2150.21   138.1 2137.88   276.2 2080.91
   305.1 2078.19   334.5 2073.68   345.6 2070.59  356.262070.769   385.8 2070.46
   409.2 2066.85   414.9 2064.88   424.52058.138   429.8 2056.89   439.6 2057.96
   446.7 2060.06   455.4 2060.62  463.192064.085   472.1 2066.22   505.5 2066.52
   510.3 2067.26   516.1 2069.89   530.5 2079.14     570 2109.82   598.6 2128.11
   620.9  2140.6  697.642179.959   766.8 2219.43  818.942251.624   839.7 2263.56
#Mann= 7 ,-1 , 0
       0      .1       0  356.26     .06       0   424.5    .045       0
   439.6     .06       0  463.19      .1       0  697.64      .1       0
  818.94      .1       0
Bank Sta=424.5,439.6
XS Rating Curve= 0 ,0
Exp/Cntr=0.3,0.1

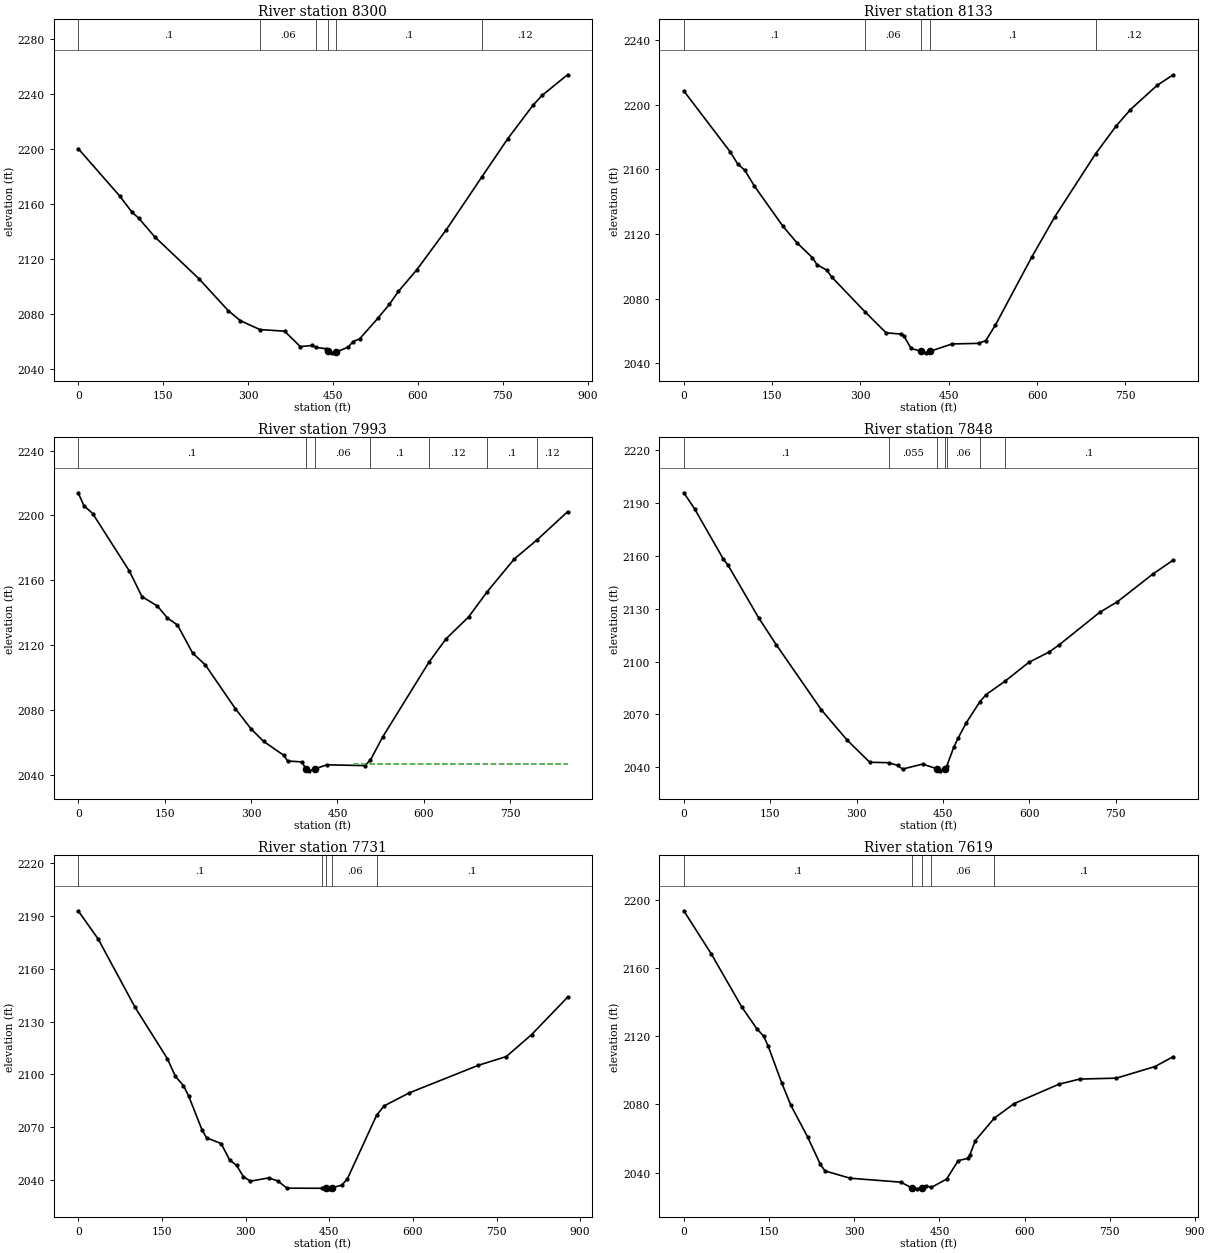
Type RM Length L Ch R = 1 ,8300    ,168.4,167.4,166.1
XS GIS Cut Line= 3
      2446386.66      586754.7622446526.56823756587091.707877984
2446581.49719905587588.025574642
#Sta/Elev= 30
       0 2200.28    73.4 2165.84    94.8 2154.23   107.1 2149.67     135 2136.31
   212.9 2105.96   264.9  2082.7   286.5 2075.34  320.862068.919   364.5 2067.73
   392.3 2056.55   412.8 2057.34  419.692056.004   436.9    2055     441 2053.45
     449 2052.01   455.82052.541   477.2 2056.26   485.2 2060.11   497.3 2062.25
   529.5 2077.23   549.6 2087.22   565.7 2096.68   597.9 2112.25   650.2 2141.41
  712.562179.499   758.8 2207.52   803.1 2231.67   819.2 2238.84   864.2 2253.86
#Mann= 6 ,-1 , 0
       0      .1       0  320.86     .06       0  419.69      .1       0
     441    .045       0   455.8      .1       0  712.56     .12       0
Bank Sta=441,455.8
XS Rating Curve= 0 ,0
Exp/Cntr=0.3,0.1

Type RM Length L Ch R = 1 ,8133    ,142.1,139.6,136.5
XS GIS Cut Line= 2
     2446286.712      586774.137     2446462.843      587586.236
#Sta/Elev= 30
       0 2208.53    79.1  2170.7    91.3 2163.47   103.6 2159.44     120 2149.63
   168.6 2124.72   192.1 2114.62   218.2  2105.5   226.4 2101.03   242.8 2097.68
     251 2093.53  308.442071.677   343.5 2058.94   369.6 2058.14   373.8 2057.05
     386 2049.29   402.92047.532   410.6 2046.56     4182047.479   455.6 2052.07
   500.6 2052.41   512.9 2054.14   529.3  2063.8   590.6 2105.56   629.8 2130.53
  699.252169.604   733.9 2186.67   758.4 2196.94   803.5 2211.88     831  2218.5
#Mann= 5 ,-1 , 0
       0      .1       0  308.44     .06       0   402.9    .045       0
     418      .1       0  699.25     .12       0
Bank Sta=402.9,418
XS Rating Curve= 0 ,0
Exp/Cntr=0.3,0.1

Type RM Length L Ch R = 1 ,7993    ,145.4,145.8,145.4
XS GIS Cut Line= 2
     2446069.524      586822.517     2446421.118      587595.554
#Sta/Elev= 30
       0 2213.99     9.8 2206.09    25.2 2201.18    88.9 2165.74   110.8 2149.99
   137.2 2144.33   154.8 2136.94   172.3 2132.54   198.7 2115.26   220.7 2107.97
   272.8 2081.05     300 2068.59   321.7 2060.92   356.9 2052.31   363.4 2048.81
   387.6 2048.29   395.42044.179   400.8 2042.77   410.42043.905   431.6 2046.49
   497.5 2045.98  507.242049.424   528.2  2063.5  608.512109.541   638.1 2123.93
   677.9 2137.68  709.782153.048   756.7 2173.17  796.162184.926   849.2 2202.27
#Mann= 7 ,-1 , 0
       0      .1       0   395.4    .045       0   410.4     .06       0
  507.24      .1       0  608.51     .12       0  709.78      .1       0
  796.16     .12       0
#XS Ineff= 2 , 0
                          478.59         2047.21
Permanent Ineff=
       F       F
Bank Sta=395.4,410.4
XS Rating Curve= 0 ,0
Exp/Cntr=0.3,0.1

Type RM Length L Ch R = 1 ,7848    ,115.2,117,118.9
XS GIS Cut Line= 2
     2445955.694      586889.145     2446305.327      587663.481
#Sta/Elev= 30
       0 2195.77    18.6 2186.74    68.3 2158.36    77.1 2154.51   129.7 2124.96
   160.5 2109.56   238.8 2072.61   283.3 2055.53   322.8 2042.86  355.472042.615
   371.1  2041.1   379.9 2038.99   414.6 2041.82     4392039.232   445.7 2037.99
     4542039.257  456.662040.776     469 2051.58   476.4 2056.61   490.2 2065.11
  513.812077.102   524.7 2081.21  557.862088.886     599 2099.53   634.4 2105.43
     652 2109.55   722.2 2127.94   752.9 2133.94   814.3 2149.64   849.6 2157.53
#Mann= 7 ,-1 , 0
       0      .1       0  355.47    .055       0     439    .045       0
     454    .055       0  456.66     .06       0  513.81      .1       0
  557.86      .1       0
Bank Sta=439,454
XS Rating Curve= 0 ,0
Exp/Cntr=0.3,0.1

Type RM Length L Ch R = 1 ,7731    ,111.6,111.7,107.1
XS GIS Cut Line= 3
     2445915.849       586900.692446078.49088007587522.628959008
 2446265.4343773587664.151690185
#Sta/Elev= 30
       0 2192.92    35.9 2176.85     102 2138.05   159.9 2108.93   174.3 2098.88
   188.8 2093.55   198.2  2087.6   221.9 2068.55   230.1 2063.96   256.3 2060.71
   271.5  2051.4   283.9 2048.28   296.3  2041.9   308.7 2039.34   341.8  2041.2
   358.3 2039.36   374.3 2035.36  437.082035.299     4452035.233   449.3 2034.98
   455.32035.619   472.6  2037.1   482.4 2040.51  535.122076.799   548.5  2082.1
   593.4 2089.46   717.2 2105.12   767.6 2110.13   812.8 2122.55   877.3 2143.78
#Mann= 5 ,-1 , 0
       0      .1       0  437.08     .06       0     445    .045       0
   455.3     .06       0  535.12      .1       0
Bank Sta=445,455.3
XS Rating Curve= 0 ,0
Exp/Cntr(USF)=0,0
Exp/Cntr=0.3,0.1

Type RM Length L Ch R = 1 ,7619    ,99.7,101.6,101.6
XS GIS Cut Line= 4
2445892.39256937586906.945048168 2445891.5400003  587149.8649041
2445953.38991671  587406.91056792446182.55498907587676.661786521
#Sta/Elev= 30
       0 2193.76    48.5 2168.36   102.5 2136.99   128.4 2124.57   140.4 2120.19
   148.4  2114.4   172.4 2092.64   188.4 2079.56   218.1 2060.81   240.4  2044.8
   248.6 2040.98   292.6 2036.71   382.2 2034.38   400.92031.038   409.6 2030.46
   418.6 2031.09   425.5 2032.32   435.92031.321   462.5 2036.16   483.1 2047.05
   499.5 2048.33   503.6  2050.4   513.1 2058.77  546.52 2071.97   581.4  2080.5
   660.1 2091.88   696.8 2094.92   761.5 2095.47   829.5 2102.29   861.3 2108.05
#Mann= 5 ,-1 , 0
       0      .1       0   400.9    .045       0   418.6      .1       0
   435.9     .06       0  546.52      .1       0
Bank Sta=400.9,418.6
XS Rating Curve= 0 ,0
Exp/Cntr=0.3,0.1