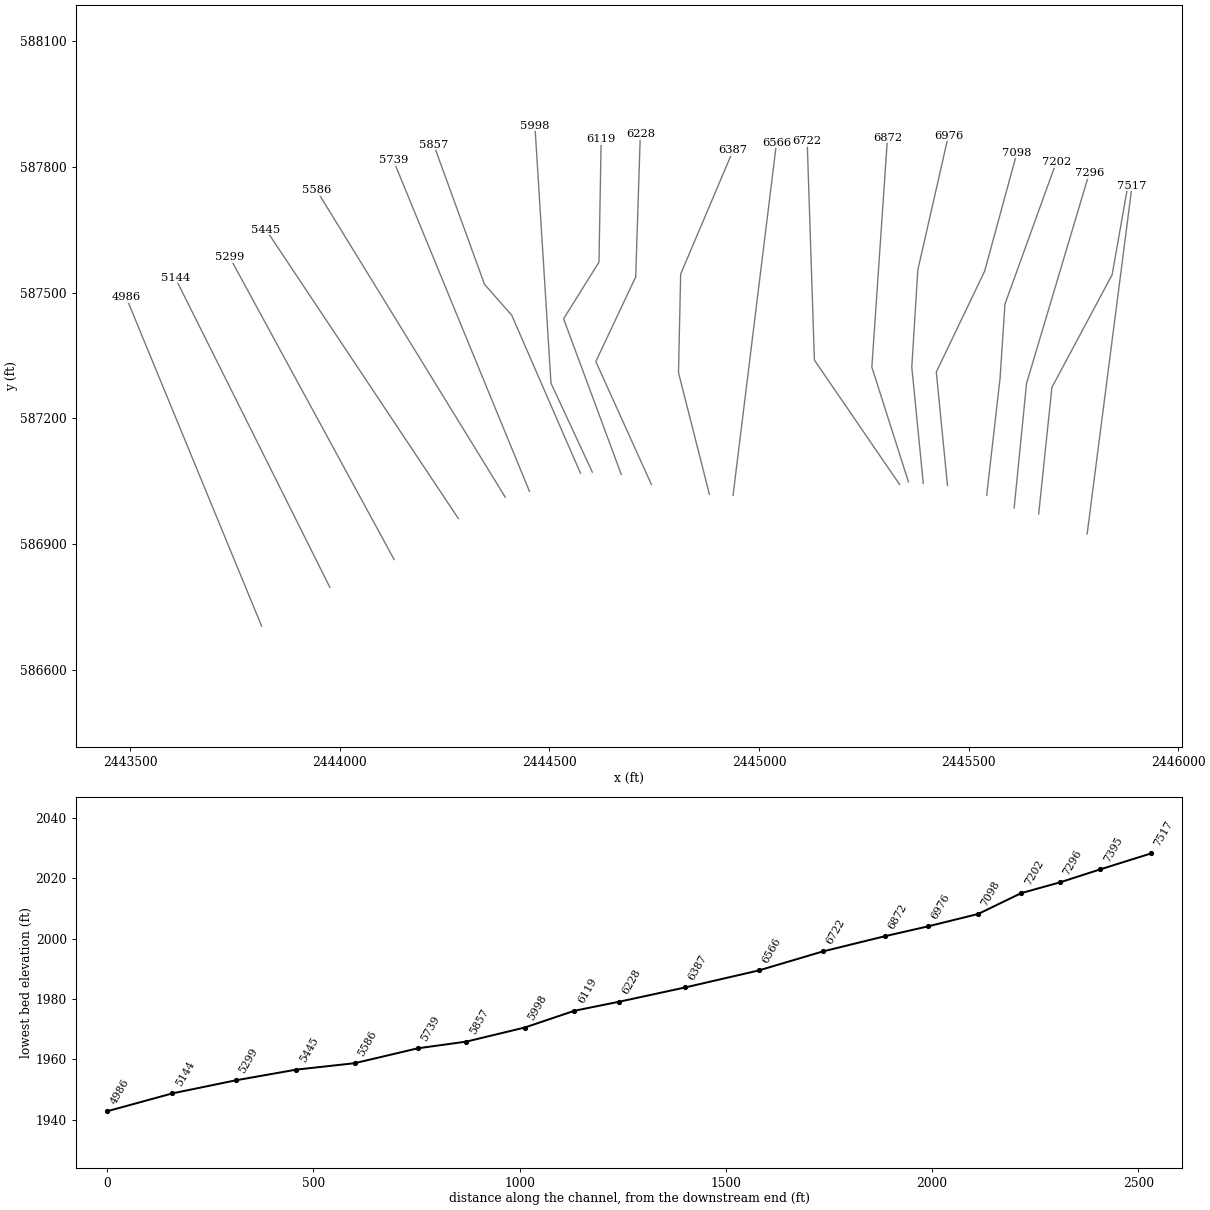
HEC-RAS study DRYRN2.prj: DRYRN2

--- DRYRN2.g01 (geometry) --- (continued)

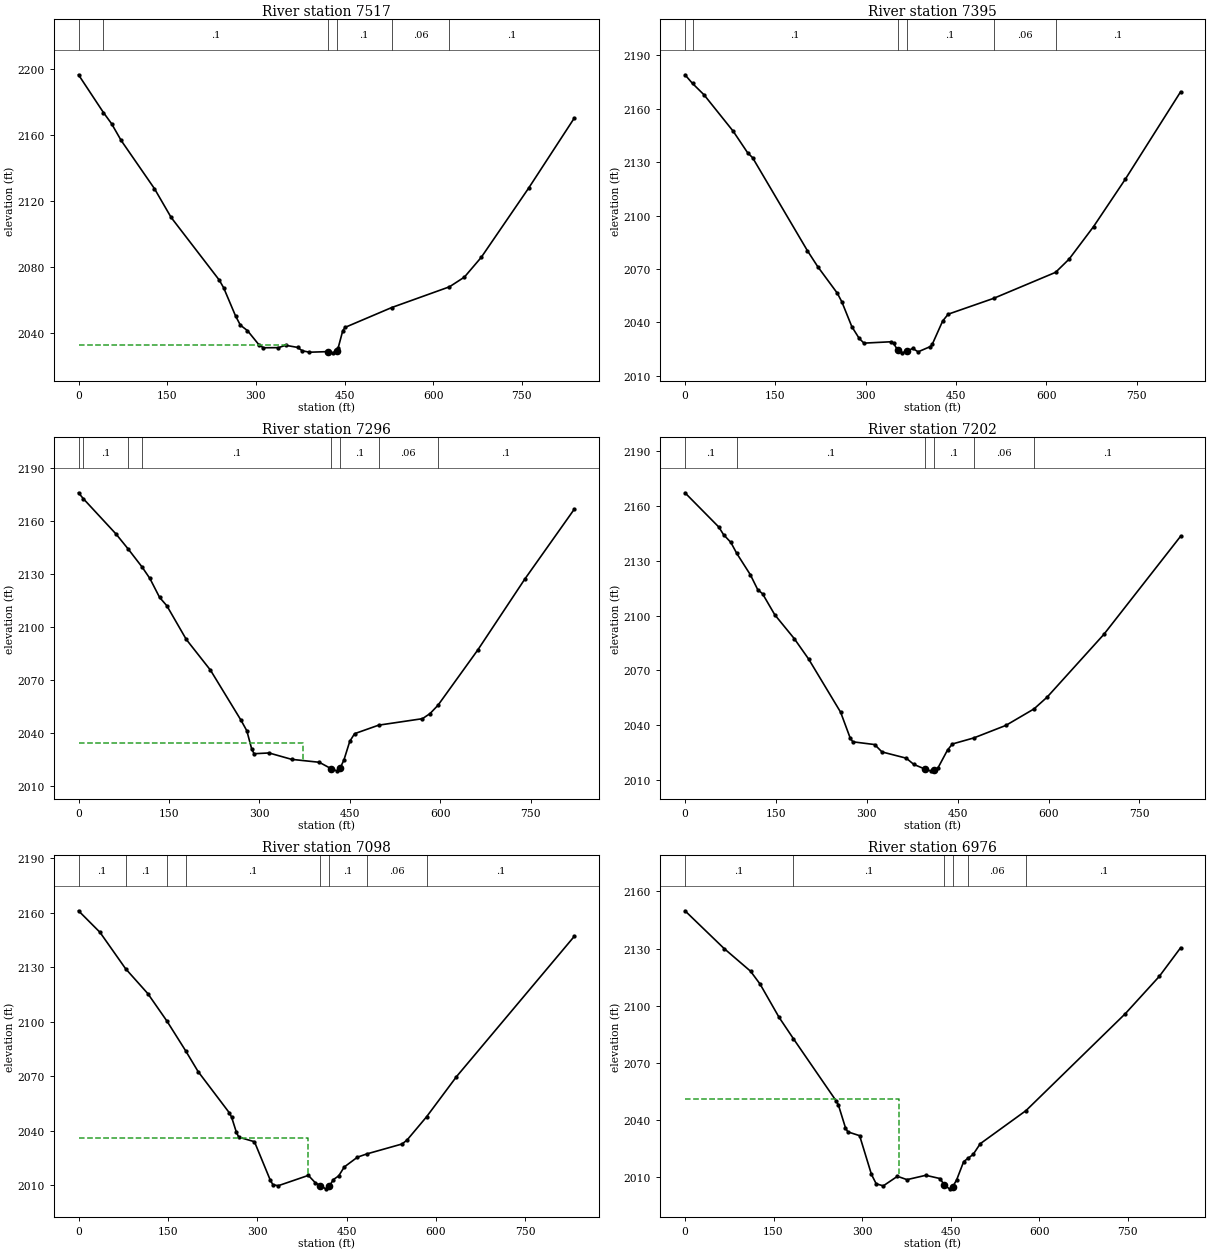
Type RM Length L Ch R = 1 ,7517    ,126.7,122.7,118
XS GIS Cut Line= 2
2445783.12588923586923.9283370822445890.37488923587755.523337082
#Sta/Elev= 30
       0 2196.78   42.132173.905    55.9 2167.14    72.1 2156.98   128.5 2127.72
   156.7 2110.28   237.9  2072.4   245.5 2067.66   265.6 2050.61   273.8 2044.98
   285.8 2041.65   305.7 2032.86   312.9 2031.26   338.2 2031.32   350.3 2032.76
   370.5 2031.48   378.5 2029.44   390.6 2028.56   421.92028.919   430.8 2028.18
   436.62029.489     439 2030.83   447.1 2041.69   451.1 2043.64  529.942055.656
   627.52068.213   652.8  2074.1   681.3 2086.08   761.7 2128.18   838.5 2170.41
#Mann= 6 ,-1 , 0
       0      .1       0   42.13      .1       0   421.9    .045       0
   436.6      .1       0  529.94     .06       0   627.5      .1       0
#XS Ineff= 2 , 0
          352.43 2032.74
Permanent Ineff=
       F       F
Bank Sta=421.9,436.6
XS Rating Curve= 0 ,0
Exp/Cntr=0.3,0.1

Type RM Length L Ch R = 1 ,7395    ,95.7,98.6,100.5
XS GIS Cut Line= 4
2445667.47929379586971.8345633952445699.00080612  587273.5363554
2445842.77237599587542.690108292     2445880.003      587753.738
#Sta/Elev= 30
       0 2178.98   12.542174.102    31.7 2167.71      80 2147.31   104.1 2135.17
   112.2 2132.47   203.2 2080.27   220.4 2071.29   252.9 2056.38   260.4 2051.55
     277  2037.6   289.1 2031.07   297.1 2028.37   341.7 2029.13   346.2  2028.3
   353.32024.333   359.8 2022.92     3682023.733     378 2025.42     387 2023.49
   407.5 2026.47   410.4 2027.64   427.8  2040.8   436.9 2044.61  512.272053.485
   615.2  2068.1   637.6  2075.5   678.2 2093.75     731  2120.4   822.8 2169.45
#Mann= 6 ,-1 , 0
       0      .1       0   12.54      .1       0   353.3    .045       0
     368      .1       0  512.27     .06       0   615.2      .1       0
Bank Sta=353.3,368
XS Rating Curve= 0 ,0
Exp/Cntr=0.3,0.1

Type RM Length L Ch R = 1 ,7296    ,90.6,93.5,96.1
XS GIS Cut Line= 3
2445608.93266939586985.5785136342445638.50286196587283.264242334
2445788.01398398587784.529751193
#Sta/Elev= 30
       0 2176.08    7.952172.743    62.1 2152.78   82.55 2144.17  105.622133.951
   118.4 2127.54   134.5 2116.81   146.5  2112.1   178.7 2093.05   218.9  2075.6
   269.6 2047.21   279.2 2041.27   287.2 2031.05   291.2 2028.27     316 2028.71
   353.5 2025.09   399.4 2023.43   419.42019.726   428.6 2018.58   433.82020.018
   440.3 2024.75   449.9 2035.23   457.9 2039.62  497.862044.452   570.5 2048.12
   583.1 2051.01   596.32055.728   662.4 2087.09   740.1 2127.08   822.2 2166.69
#Mann= 8 ,-1 , 0
       0      .1       0    7.95      .1       0   82.55      .1       0
  105.62      .1       0   419.4    .045       0   433.8      .1       0
  497.86     .06       0   596.3      .1       0
#XS Ineff= 2 , 0
          372.15  2034.4
Permanent Ineff=
       F       F
Bank Sta=419.4,433.8
XS Rating Curve= 0 ,0
Exp/Cntr=0.3,0.1

Type RM Length L Ch R = 1 ,7202    ,109,104.5,99.7
XS GIS Cut Line= 4
  2445543.401106587016.1648009552445575.29038553587295.269267124
2445586.99272262587472.4760857982445709.18069666587810.557325835
#Sta/Elev= 30
       0 2167.34    55.9 2148.55    63.6 2144.43    75.7 2140.16   85.372134.178
   107.9 2122.44     120 2114.32     128 2112.04   148.2 2100.51   180.4 2087.43
     204  2076.3   256.9 2047.13   272.6 2033.05     277 2030.93   313.1 2029.42
   325.1 2025.39   365.2 2021.96   377.6 2018.56   396.72015.907   405.3 2015.03
   411.62015.428   417.3  2016.5   433.3 2026.43   441.3 2029.74  476.672033.058
   529.6 2039.92  576.042048.957   597.7 2055.41   691.2 2089.74     818 2143.54
#Mann= 6 ,-1 , 0
       0      .1       0   85.37      .1       0   396.7    .045       0
   411.6      .1       0  476.67     .06       0  576.04      .1       0
Bank Sta=396.7,411.6
XS Rating Curve= 0 ,0
Exp/Cntr=0.3,0.1

Type RM Length L Ch R = 1 ,7098    ,117.5,122.1,126.6
XS GIS Cut Line= 4
2445449.78240934587039.5694751192445423.16000346587310.315129087
2445538.51161185587551.048920494     2445615.562      587833.962
#Sta/Elev= 30
       0 2161.04      36 2149.21   79.042129.183   116.4 2115.48  148.462100.382
  179.752084.118   200.8 2072.62     253 2050.04     257 2047.58   265.1 2039.21
   269.1 2036.55   295.4 2034.05     322 2012.89   326.4 2010.41   335.3 2009.84
   385.9 2015.52   397.9 2011.37   406.2  2009.9   415.1 2008.13   420.92009.547
   427.9  2013.2   436.9 2015.27   446.2 2020.15   468.4 2025.56  484.292027.355
   543.4 2032.81   551.9 2035.08  584.432047.767   634.6 2069.82   832.2  2146.9
#Mann= 8 ,-1 , 0
       0      .1       0   79.04      .1       0  148.46      .1       0
  179.75      .1       0   406.2    .045       0   420.9      .1       0
  484.29     .06       0  584.43      .1       0
#XS Ineff= 2 , 0
          385.97 2036.22
Permanent Ineff=
       F       F
Bank Sta=406.2,420.9
XS Rating Curve= 0 ,0
Exp/Cntr(USF)=0,0
Exp/Cntr=0.3,0.1

Type RM Length L Ch R = 1 ,6976    ,103.4,103.5,103.1
XS GIS Cut Line= 4
2445392.04978493587044.8179502392445364.64831805587322.017466169
2445379.05801125587553.9295473742445452.03092944587874.642524881
#Sta/Elev= 30
       0 2149.78    66.4 2129.96   111.1  2118.1   127.2 2111.36   159.3 2093.98
  183.572082.783   255.8 2050.27   259.8 2048.11   271.9 2036.04   275.9 2033.88
   295.9 2031.88     316 2011.53     324 2006.65     336 2005.57     360 2010.59
   376.1 2008.83   408.1 2011.11   432.1  2009.4   439.6 2005.93   448.2 2004.01
   453.42005.002   460.2 2008.65   472.2 2018.28  480.032020.123   488.3 2022.07
   500.3 2027.67  577.852045.037   746.2 2095.88   803.6 2115.37   839.8 2130.41
#Mann= 6 ,-1 , 0
       0      .1       0  183.57      .1       0   439.6    .045       0
   453.4      .1       0  480.03     .06       0  577.85      .1       0
#XS Ineff= 2 , 0
          363.27 2051.35
Permanent Ineff=
       F       F
Bank Sta=439.6,453.4
XS Rating Curve= 0 ,0
Exp/Cntr=0.3,0.1

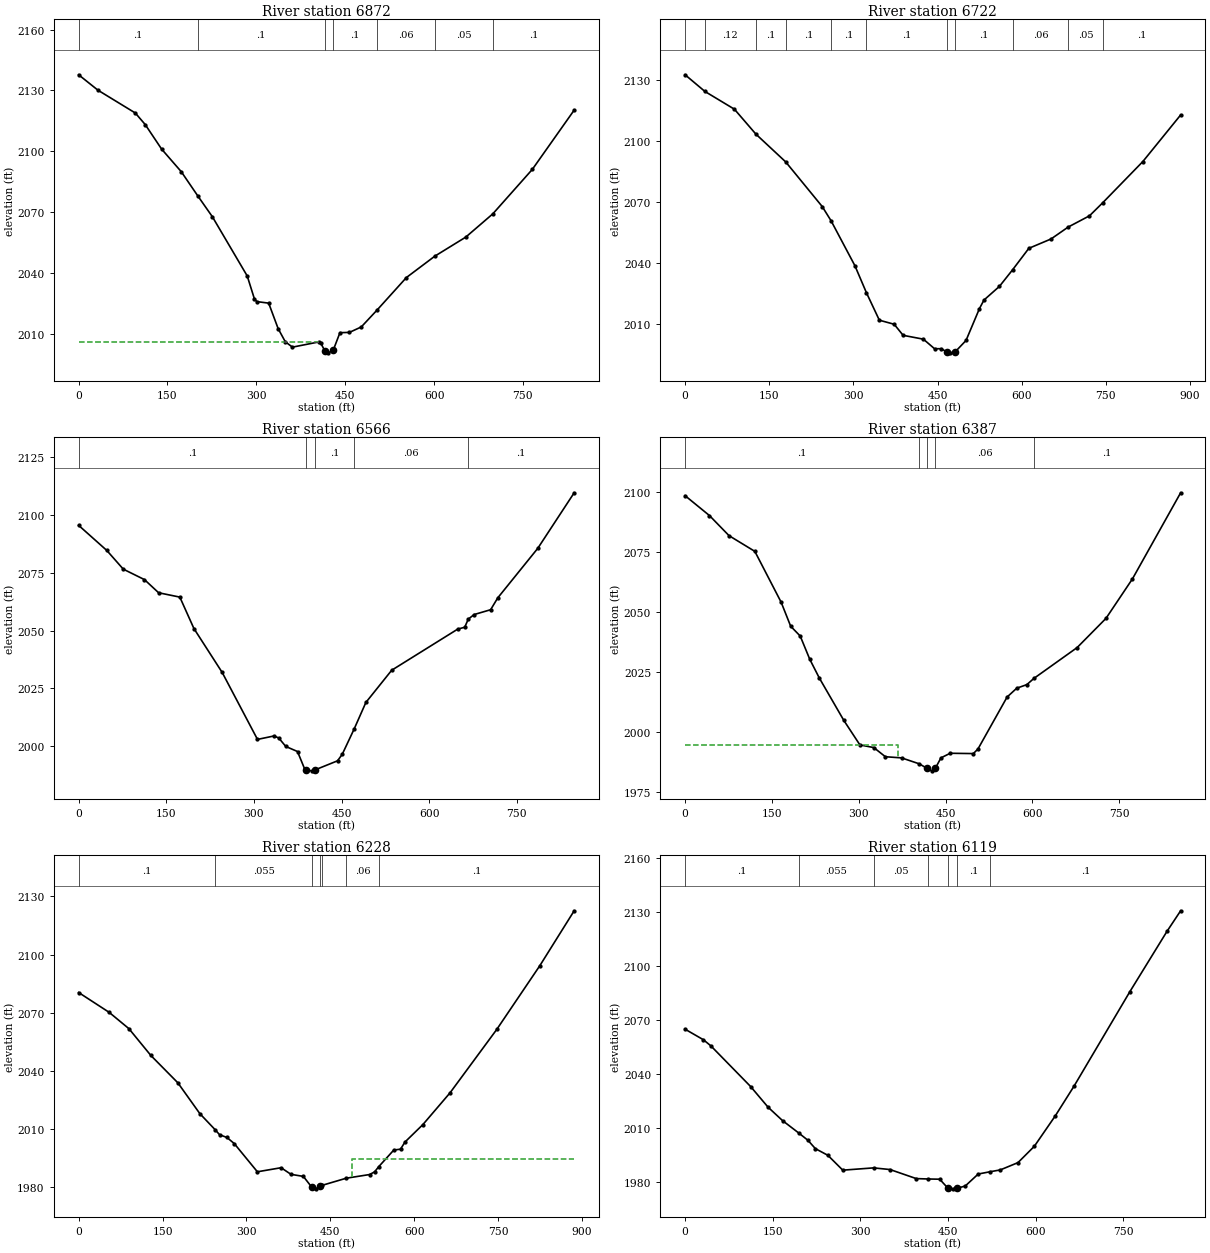
Type RM Length L Ch R = 1 ,6872    ,149.3,150.5,151.8
XS GIS Cut Line= 3
2445356.61603374 587048.216762442445269.35785895587322.017466169
2445306.70318302587869.909524881
#Sta/Elev= 30
       0 2137.74    32.7 2130.13    95.7 2118.91   112.5 2113.18   140.1 2101.13
   173.3 2089.99  200.952078.163   225.8  2067.8   284.6 2038.64   296.7 2027.37
   300.7 2026.02   320.8 2025.26   336.8  2012.7   348.8 2006.26   360.9 2003.58
     405 2006.12     409 2005.42   415.4 2001.86     421 2000.78   429.72001.999
   441.1 2010.71   457.1 2010.85   477.1 2013.53  503.422021.744   553.3 2037.87
  601.312048.403   653.5 2057.78   699.22069.249   765.8 2091.12   836.5 2120.33
#Mann= 7 ,-1 , 0
       0      .1       0  200.95      .1       0   415.4    .045       0
   429.7      .1       0  503.42     .06       0  601.31     .05       0
   699.2      .1       0
#XS Ineff= 2 , 0
          405.75 2006.17
Permanent Ineff=
       F       F
Bank Sta=415.4,429.7
XS Rating Curve= 0 ,0
Exp/Cntr=0.3,0.1

Type RM Length L Ch R = 1 ,6722    ,158.5,156.2,154.6
XS GIS Cut Line= 3
2445335.70594546587041.6185248812445132.27333885587338.735090572
2445115.02180743587861.748436605
#Sta/Elev= 30
       0 2132.49   35.332124.292    87.9 2115.56   126.32103.279  179.332089.647
   244.5 2067.67  260.152060.725   302.7  2038.6  323.322025.266   346.3 2011.79
   372.7  2009.8   388.7 2004.35   424.8 2002.46   444.7 1997.76   456.8 1997.77
     4671996.089   472.8 1995.74   481.31996.179   500.8 2001.82   524.8 2017.54
   532.8  2021.7   560.4 2028.44  583.762036.559   612.8 2047.14   652.3 2051.73
  683.022057.617   720.9 2063.13  744.252069.481   816.1 2089.84   883.4 2112.72
#Mann= 11 ,-1 , 0
       0      .1       0   35.33     .12       0   126.3      .1       0
  179.33      .1       0  260.15      .1       0  323.32      .1       0
     467    .045       0   481.3      .1       0  583.76     .06       0
  683.02     .05       0  744.25      .1       0
Bank Sta=467,481.3
XS Rating Curve= 0 ,0
Exp/Cntr=0.3,0.1

Type RM Length L Ch R = 1 ,6566    ,177,178.2,179.4
XS GIS Cut Line= 2
2444938.12712202 587015.52423756 2445041.8130835587857.308911724
#Sta/Elev= 30
       0 2095.47    48.2 2084.63    76.4 2076.55   112.7 2072.02   136.9 2066.35
   173.2 2064.47   197.3  2050.9   245.7 2031.92   306.1    2003   334.3 2004.48
   342.4 2003.64   354.5 1999.96   374.6 1997.76   386.7  1990.3  389.58 1989.79
   398.8 1989.42   404.3  1989.8   443.1 1993.75   451.2 1996.58  471.662007.563
   491.6 2018.96   535.8 2032.88   648.7 2050.63   660.8 2051.46  666.822054.954
   676.9 2056.94   705.1 2059.02   717.4 2064.17   785.8 2085.54   848.1 2109.54
#Mann= 5 ,-1 , 0
       0      .1       0  389.58    .045       0   404.3      .1       0
  471.66     .06       0  666.82      .1       0
Bank Sta=389.58,404.3
XS Rating Curve= 0 ,0
Exp/Cntr=0.3,0.1

Type RM Length L Ch R = 1 ,6387    ,164.3,159.5,154.1
XS GIS Cut Line= 4
2444881.62078493 587018.590237562444807.95142542587308.643366646
2444813.11934833587544.1748459422444938.49793422587839.958475119
#Sta/Elev= 30
       0 2098.28    42.1 2090.01    75.9 2081.65   120.5 2075.11   165.9 2053.97
   182.4 2043.97   198.9 2039.87   215.4 2030.21   231.9 2022.41   274.2 2004.79
     302 1994.59     326 1993.48     346 1989.67     374 1989.19  404.411986.726
   417.71984.887     426  1983.8   432.51984.925     442  1989.2     458 1991.11
     498 1990.98     506 1992.91   556.3 2014.51     573 2018.19   590.4 2019.67
  602.662022.269   677.3 2035.09   727.2 2047.26   772.9 2063.69   856.1 2099.49
#Mann= 5 ,-1 , 0
       0      .1       0  404.41     .06       0   417.7    .045       0
   432.5     .06       0  602.66      .1       0
#XS Ineff= 2 , 0
          367.37 1994.73
Permanent Ineff=
       F       F
Bank Sta=417.7,432.5
XS Rating Curve= 0 ,0
Exp/Cntr=0.3,0.1

Type RM Length L Ch R = 1 ,6228    ,110,108.7,107.2
XS GIS Cut Line= 4
2444743.30115576587041.6855248812444610.68345746587335.391565692
2444705.83612202587537.3714590992444716.86659066587877.627199045
#Sta/Elev= 30
       0 2080.43    54.5 2070.21    89.9 2061.77   129.1 2047.94   177.4 2033.82
   216.8 2017.88  244.182009.577     252 2007.02   265.2  2005.6   278.3 2002.44
   319.6 1987.89     362 1989.99   379.7 1986.57   401.8 1985.51   417.1 1979.84
   423.9 1979.09   431.81980.333  434.921980.862   478.51984.577   520.2 1986.47
   529.2 1987.86  536.581990.545   563.5 1999.12   575.5 1999.56   583.5 2003.26
   615.5 2012.26     664 2028.63   747.6 2061.38   824.4 2094.19     886 2122.62
#Mann= 7 ,-1 , 0
       0      .1       0  244.18    .055       0   417.1    .045       0
   431.8    .055       0  434.92      .1       0   478.5     .06       0
  536.58      .1       0
#XS Ineff= 2 , 0
                          489.35         1994.26
Permanent Ineff=
       F       F
Bank Sta=417.1,431.8
XS Rating Curve= 0 ,0
Exp/Cntr=0.3,0.1

Type RM Length L Ch R = 1 ,6119    ,114.6,120.7,128
XS GIS Cut Line= 4
2444671.23109475587066.1516244032444533.78238521587437.369074552
2444618.19469666587572.6611492842444623.44195501      587865.757
#Sta/Elev= 30
       0 2064.91    31.2 2059.07      44 2055.68   112.2 2033.01   142.1 2021.51
   166.8 2014.07  194.392007.205   210.3 2003.11   223.1 1998.45   244.4 1994.76
     270 1986.48  322.761987.752     351 1986.82   395.8 1981.79  416.631981.566
   435.9 1981.45     450 1976.48   459.5 1976.09   464.91976.335   479.7 1977.67
   501.9 1984.33  522.691985.633   539.6 1986.61     570 1990.68     598 1999.77
     634 2016.76     666 2033.25   761.7 2085.86   825.1 2119.34   848.5  2130.8
#Mann= 7 ,-1 , 0
       0      .1       0  194.39    .055       0  322.76     .05       0
  416.63      .1       0     450    .045       0   464.9      .1       0
  522.69      .1       0
Bank Sta=450,464.9
XS Rating Curve= 0 ,0
Exp/Cntr=0.3,0.1

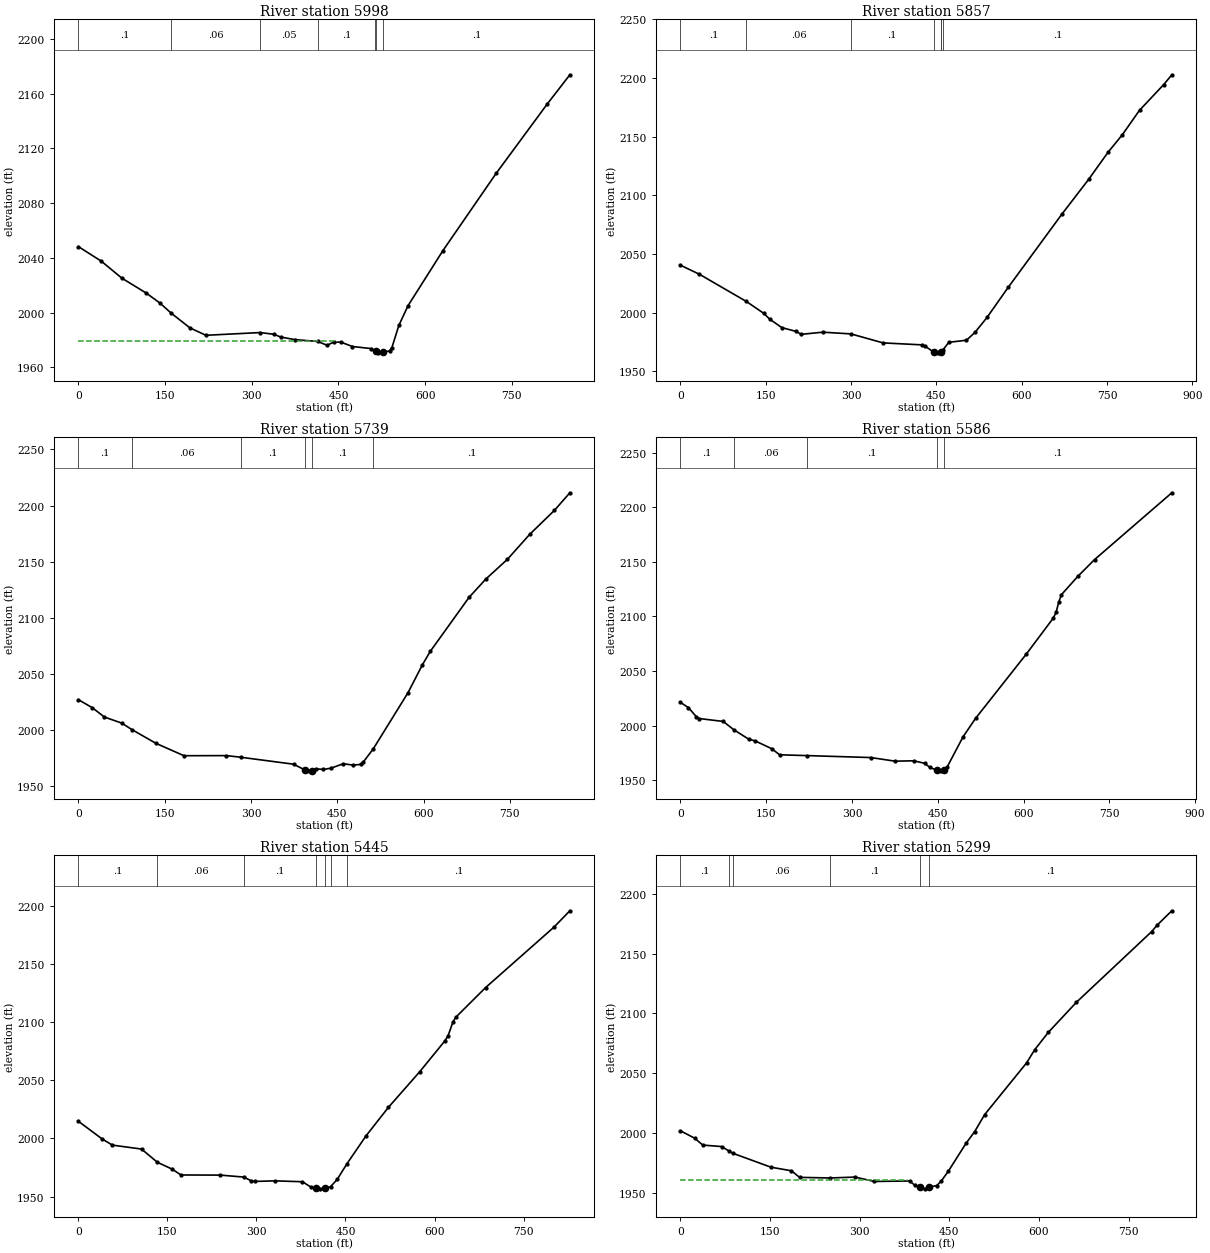
Type RM Length L Ch R = 1 ,5998    ,134.4,141.3,149.4
XS GIS Cut Line= 3
2444602.32464526 587071.253100122444503.69066128587283.566930041
2444465.24012516587898.775508082
#Sta/Elev= 30
       0 2048.22    39.8 2037.51    75.1 2025.18   117.7 2014.15   141.3 2006.86
  160.84 1999.46     193 1988.77   220.7 1983.37  314.161985.356   338.1 1984.14
   350.1 1982.07   374.9 1980.19  414.021978.844   430.3 1976.08   442.3 1978.45
   454.3 1978.34   474.3 1975.16   506.4 1973.65  513.881972.241   514.91971.879
   518.4 1970.53   527.61971.132   538.5 1971.92   542.5 1974.33   554.5 1990.55
   570.5 2005.07   630.6 2045.18   722.8 2101.74     811 2152.35   850.5 2173.92
#Mann= 7 ,-1 , 0
       0      .1       0  160.84     .06       0  314.16     .05       0
  414.02      .1       0  513.88      .1       0   514.9    .045       0
   527.6      .1       0
#XS Ineff= 2 , 0
          447.37 1979.42
Permanent Ineff=
       F       F
Bank Sta=514.9,527.6
XS Rating Curve= 0 ,0
Exp/Cntr(USF)=0,0
Exp/Cntr=0.3,0.1

Type RM Length L Ch R = 1 ,5857    ,121.8,117.8,115.1
XS GIS Cut Line= 4
2444574.03212202587068.6481990452444410.07196463587445.727886753
2444344.96878971587519.8066244032444223.96592297587852.666149284
#Sta/Elev= 30
       0 2040.54    33.5 2032.79  116.082009.615   146.9  1999.4     157 1994.54
   178.3 1987.39   203.6 1984.11   212.3 1981.64   250.5 1983.47  299.861982.011
   356.3 1974.35     424 1972.69   429.3  1971.9   445.3 1966.48   453.5 1965.88
   457.6 1966.43  457.741966.478  461.921968.546   471.9 1974.85     503 1976.63
   517.9 1983.27   539.1 1996.01   576.5 2021.77     671 2084.17   718.3 2113.96
   751.9 2136.74   776.9 2151.57   807.2 2172.46   849.8 2194.39     864 2202.71
#Mann= 7 ,-1 , 0
       0      .1       0  116.08     .06       0  299.86      .1       0
   445.3    .045       0   457.6      .1       0  457.74      .1       0
  461.92      .1       0
Bank Sta=445.3,457.6
XS Rating Curve= 0 ,0
Exp/Cntr=0.3,0.1

Type RM Length L Ch R = 1 ,5739    ,149.8,153,155.2
XS GIS Cut Line= 2
     2444452.223      587025.607     2444127.546      587815.668
#Sta/Elev= 30
       0 2027.03    24.4 2019.83    45.2 2011.56    75.4 2006.16   93.062000.375
   134.7 1988.17   183.5 1977.13   257.3 1977.23  282.871975.728   373.9 1969.58
   394.61964.202   401.4 1963.66   405.3 1963.94   412.7 1965.46   425.7 1964.92
   438.7 1965.97   460.3    1970   477.6 1968.75   490.6  1969.4   494.9 1971.33
   512.5 1983.26     573 2033.39   597.5 2057.75   611.6 2070.11   678.9 2118.14
   707.8 2134.33   745.7 2152.12   784.4 2174.33   827.4 2195.71   854.2 2211.36
#Mann= 6 ,-1 , 0
       0      .1       0   93.06     .06       0  282.87      .1       0
   394.6    .045       0   405.3      .1       0   512.5      .1       0
Bank Sta=394.6,405.3
XS Rating Curve= 0 ,0
Exp/Cntr=0.3,0.1

Type RM Length L Ch R = 1 ,5586    ,140.9,141.3,141.5
XS GIS Cut Line= 2
2444394.43307226587011.543199045     2443944.683       587743.76
#Sta/Elev= 30
       0  2021.4    13.9 2016.66      28 2008.21    32.7 2006.61    74.9 2003.94
   93.431996.345   119.3 1987.75   130.9  1986.1     160 1978.91   173.5 1973.41
  221.481972.679   333.1 1970.89   375.3 1967.58   408.2 1967.92     427 1965.64
   436.3 1961.88   447.9 1959.34   455.1 1958.73   461.1 1959.27   466.7 1962.51
   494.4 1989.98   516.1 2006.74   604.9 2065.62   652.3 2098.72     657 2104.03
   661.7  2113.3   666.3 2119.97     695 2136.75   724.1 2152.02   859.3 2213.21
#Mann= 5 ,-1 , 0
       0      .1       0   93.43     .06       0  221.48      .1       0
   447.9    .045       0   461.1      .1       0
Bank Sta=447.9,461.1
XS Rating Curve= 0 ,0
Exp/Cntr=0.3,0.1

Type RM Length L Ch R = 1 ,5445    ,147.1,146.1,144.9
XS GIS Cut Line= 2
     2444282.687      586960.4572443823.81219905587649.795436605
#Sta/Elev= 30
       0 2014.63      40 1999.45    57.3 1994.17   106.3 1990.79  132.911979.473
   158.3 1973.44   172.7 1968.52   239.1 1968.41  278.911966.703   290.9 1963.52
   296.7 1962.97   331.3 1963.48   377.5  1962.7   392.7 1957.82   400.6 1957.08
   407.1 1956.61     415 1957.11  424.921958.457     436 1964.71  452.681978.307
   484.5 2002.04   522.4 2026.66   575.3 2057.33   616.9 2083.38   622.7 2087.95
   631.3 2100.25   636.1 2104.14   686.1 2129.53   801.1 2181.36   828.1 2195.51
#Mann= 7 ,-1 , 0
       0      .1       0  132.91     .06       0  278.91      .1       0
   400.6    .045       0     415      .1       0  424.92      .1       0
  452.68      .1       0
Bank Sta=400.6,415
XS Rating Curve= 0 ,0
Exp/Cntr=0.3,0.1

Type RM Length L Ch R = 1 ,5299    ,154.7,154.5,153.4
XS GIS Cut Line= 2
     2444129.406      586862.495     2443736.653      587584.868
#Sta/Elev= 30
       0 2001.72    23.8 1995.51    37.5 1989.74    69.3 1988.49   80.611984.934
   88.381982.758   151.3 1971.25   185.9 1968.19   199.3  1962.7  250.631962.201
   292.4 1962.93   324.5 1959.25   383.5 1959.69   392.6 1955.94   401.5 1954.29
   408.6 1953.09   416.51954.518     429 1955.88   436.6  1959.7   448.4 1967.94
   477.8 1991.16   492.4 2001.05   509.1  2015.3   579.2 2058.58   592.9 2069.67
   615.6 2084.16   662.7  2109.4   788.6  2168.6   797.7 2173.99   822.2 2185.97
#Mann= 6 ,-1 , 0
       0      .1       0   80.61     .05       0   88.38     .06       0
  250.63      .1       0   401.5    .045       0   416.5      .1       0
#XS Ineff= 2 , 0
          379.63 1960.14
Permanent Ineff=
       F       F
Bank Sta=401.5,416.5
XS Rating Curve= 0 ,0
Exp/Cntr=0.3,0.1

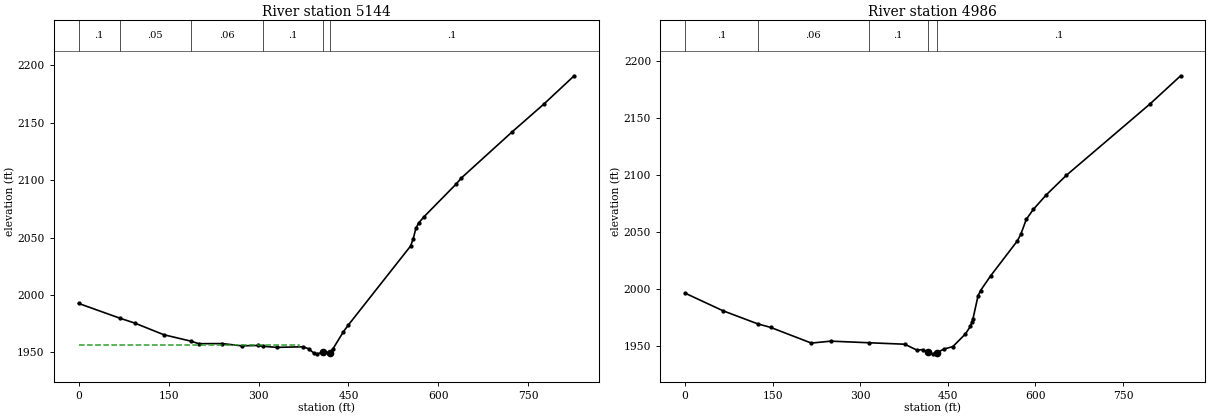
Type RM Length L Ch R = 1 ,5144    ,158.8,158,157.1
XS GIS Cut Line= 2
     2443975.998       586796.192443606.82106101587535.502199045
#Sta/Elev= 30
       0 1992.62   68.181979.884    93.2 1975.59   142.2 1965.35  187.781959.713
   200.5 1957.56   239.3 1957.68   271.8  1955.7   298.7 1956.03  307.381955.349
     330 1954.37   374.7 1954.89   383.6 1953.11   392.5 1949.31     397 1948.74
     4081950.155   419.4 1949.84   423.8 1952.81   441.7 1968.09   449.7 1973.79
   553.5 2042.54   557.9 2048.73   562.4 2057.93   566.9 2062.58   575.8 2068.02
   629.5 2096.53   638.4 2101.91   723.4  2142.2     776 2166.26   826.4 2190.82
#Mann= 6 ,-1 , 0
       0      .1       0   68.18     .05       0  187.78     .06       0
  307.38      .1       0     408    .045       0   419.4      .1       0
#XS Ineff= 2 , 0
             367 1956.11
Permanent Ineff=
       F       F
Bank Sta=408,419.4
XS Rating Curve= 0 ,0
Exp/Cntr=0.3,0.1

Type RM Length L Ch R = 1 ,4986    ,170.2,169.4,167.9
XS GIS Cut Line= 2
2443813.25277343586703.4653632482443490.03875119       587488.23
#Sta/Elev= 30
       0 1996.09    64.8 1980.66  124.881969.055   146.3 1966.08   216.2 1952.27
   249.5 1953.97  314.451952.573   376.3 1951.27   397.5 1945.94   406.7 1946.56
   415.7 1944.29   423.9 1942.83   430.71943.668   443.5 1947.08   458.5 1949.15
   480.1 1960.27   488.7 1967.04   491.1 1970.39   493.1 1973.75   501.7 1993.69
     506 1998.39   523.1 2011.17   569.1    2042   575.1 2047.95   584.4 2060.95
   596.6 2069.73   618.5 2082.33   653.1 2099.58   795.9 2162.01   848.7 2186.89
#Mann= 5 ,-1 , 0
       0      .1       0  124.88     .06       0  314.45      .1       0
   415.7    .045       0   430.7      .1       0
Bank Sta=415.7,430.7
XS Rating Curve= 0 ,0
Exp/Cntr=0.3,0.1