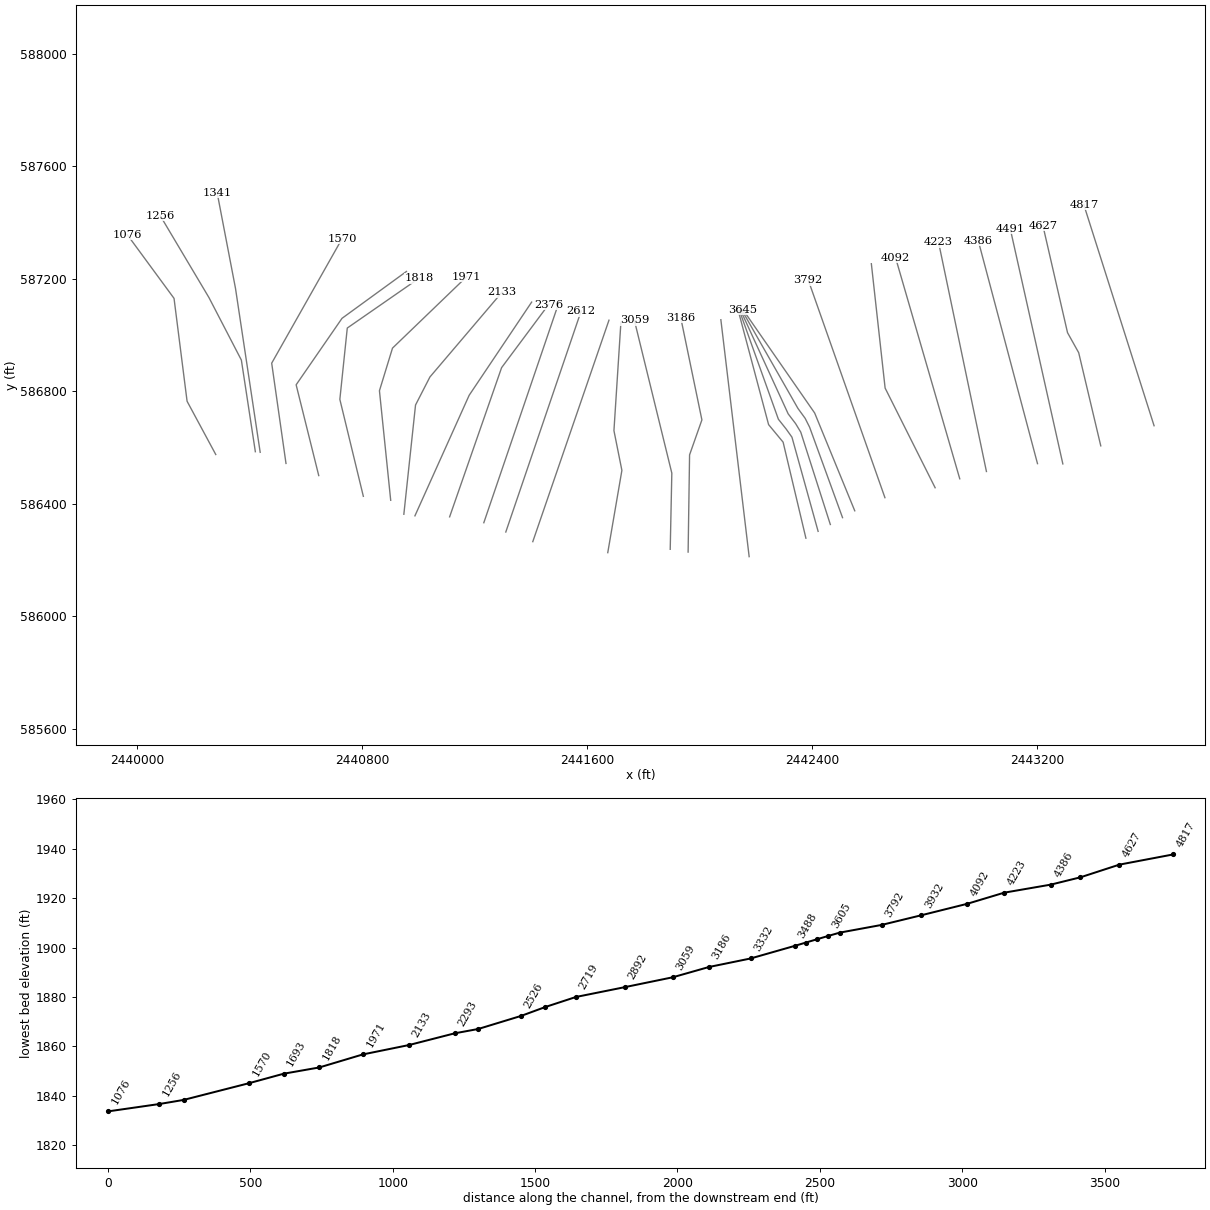
HEC-RAS study DRYRN2.prj: DRYRN2

--- DRYRN2.g01 (geometry) --- (continued)

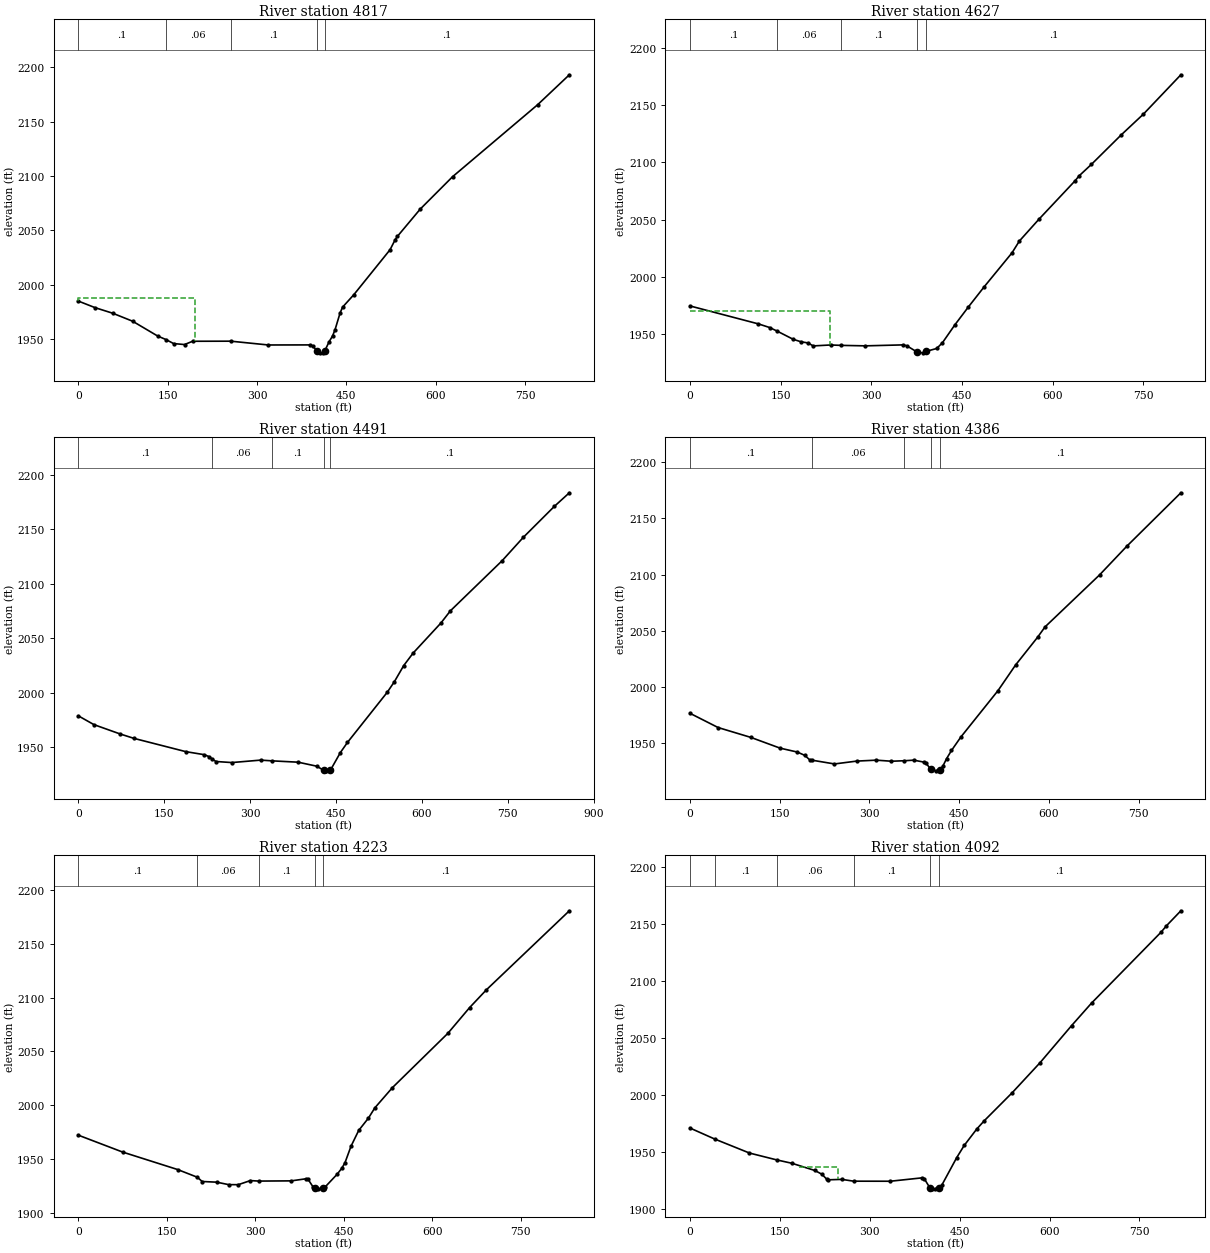
Type RM Length L Ch R = 1 ,4817    ,187.3,189.8,191.8
XS GIS Cut Line= 2
2443616.26504976586676.5911492842443366.39639162587462.320138037
#Sta/Elev= 30
       0  1985.2    28.2 1979.14    57.5 1974.09    91.1 1966.72   133.1 1953.15
  146.871949.947   159.9 1946.23   178.2 1945.32   191.8 1948.34  255.821948.422
   319.1 1944.93   389.1    1945   393.3 1944.19   400.91939.251   405.9 1937.72
   410.1 1937.83   413.6 1939.32     421 1947.88   426.9 1953.27   431.1 1959.13
   439.5 1974.35   443.7 1979.69   462.4 1990.98   523.4 2032.36   531.8 2041.36
   535.6 2044.52   574.1 2069.65   628.3 2099.31   771.3 2165.44   824.5 2192.89
#Mann= 5 ,-1 , 0
       0      .1       0  146.87     .06       0  255.82      .1       0
   400.9    .045       0   413.6      .1       0
#XS Ineff= 2 , 0
          196.12 1988.47
Permanent Ineff=
       F       F
Bank Sta=400.9,413.6
XS Rating Curve= 0 ,0
Exp/Cntr=0.3,0.1

Type RM Length L Ch R = 1 ,4627    ,140,136.6,132
XS GIS Cut Line= 4
2443426.68619257586605.0859887532443348.17881382586936.272344047
2443308.44192934587007.492522092     2443221.023       587387.55
#Sta/Elev= 30
       0 1974.55   113.4 1958.83   131.9 1955.67  144.371952.518   170.9 1945.37
   183.3  1943.3   195.6 1942.17   203.8 1939.61   232.6 1940.44  249.681940.099
   290.1 1939.67   353.1 1940.53   358.8 1939.68   375.81934.241     385 1933.57
   390.61934.847   408.1 1937.38   417.6 1942.39   438.2 1958.05   460.3 1973.51
     487  1991.5   532.6 2020.89   544.9 2031.27   577.1 2050.23   637.2 2083.99
   643.4 2088.06     664  2098.2   713.2 2123.91   750.1 2142.16   811.9 2176.45
#Mann= 5 ,-1 , 0
       0      .1       0  144.37     .06       0  249.68      .1       0
   375.8    .045       0   390.6      .1       0
#XS Ineff= 2 ,-1
       0  231.92 1969.92  232.32  341.011939.089
Permanent Ineff=
       F       F
Bank Sta=375.8,390.6
XS Rating Curve= 0 ,0
Exp/Cntr=0.3,0.1

Type RM Length L Ch R = 1 ,4491    ,103.8,104.3,104.6
XS GIS Cut Line= 2
2443291.80134833586540.8731877982443104.57469019587377.657524881
#Sta/Elev= 30
       0 1978.89    27.2 1970.84    72.3  1962.4    96.9 1958.26   187.6 1946.06
   219.9 1943.27   228.1 1941.51  234.061939.089   240.3 1937.01     268 1936.04
   318.2 1938.28  338.841937.595   383.8 1936.38   416.6 1932.67   428.3 1928.91
     433 1928.44   438.8 1929.09   441.2 1929.97   457.6 1945.24   469.9 1954.49
   539.3 2000.47   551.8 2010.19   568.2 2025.07   584.6 2036.53   633.1 2064.09
   649.8 2075.36   740.4 2121.49   777.2 2142.84   831.2 2171.16   857.5 2183.69
#Mann= 5 ,-1 , 0
       0      .1       0  234.06     .06       0  338.84      .1       0
   428.3    .045       0   438.8      .1       0
#XS Ineff= 2 , 0
          379.37 1934.91
Permanent Ineff=
       F       F
Bank Sta=428.3,438.8
XS Rating Curve= 0 ,0
Exp/Cntr=0.3,0.1

Type RM Length L Ch R = 1 ,4386    ,164,163.6,162.6
XS GIS Cut Line= 2
     2443201.635      586541.881     2442990.913      587334.711
#Sta/Elev= 30
       0 1976.65    47.1 1963.96   102.1 1955.15   150.6 1945.66   179.6 1942.15
     192 1939.21   200.3 1935.18  204.43  1934.9   241.6  1931.6   278.9 1934.14
   311.3 1934.96   336.8 1934.01   358.51934.453   374.1 1934.96   390.6 1933.28
   394.8    1932   402.81926.777   411.3 1925.47   417.8 1926.54   422.5 1929.44
     429  1936.4   437.1 1943.57   452.7  1955.5   514.8 1996.77   544.2 2019.57
     581 2044.24   593.4 2053.42   684.5 2099.63   730.2 2125.22   820.4 2172.66
#Mann= 5 ,-1 , 0
       0      .1       0  204.43     .06       0   358.5      .1       0
   402.8    .045       0   417.8      .1       0
#XS Ineff= 2 , 0
          387.31 1931.45
Permanent Ineff=
       F       F
Bank Sta=402.8,417.8
XS Rating Curve= 0 ,0
Exp/Cntr=0.3,0.1

Type RM Length L Ch R = 1 ,4223    ,129,130.2,131
XS GIS Cut Line= 2
2443020.03733708586513.9140497612442849.68777846 587329.09676244
#Sta/Elev= 30
       0 1972.06    75.1 1956.37   168.4 1940.13  201.611933.021     210 1929.03
   234.5 1928.41   254.9 1926.12   271.2 1926.08   291.7 1929.88  305.831929.422
   361.1 1929.62   385.6 1931.52   389.7 1930.95   397.9 1924.11  400.94 1922.74
   406.1 1922.21   415.1 1922.88   418.5 1923.93   438.8 1935.72   446.9 1941.42
   452.3 1946.63   462.4 1961.76   475.5 1976.51   491.9 1987.89   502.9  1997.5
   532.7 2016.29   626.7 2066.72   663.5 2090.59   692.2 2107.24   832.8 2180.63
#Mann= 5 ,-1 , 0
       0      .1       0  201.61     .06       0  305.83      .1       0
  400.94    .045       0   415.1      .1       0
#XS Ineff= 2 , 0
          387.04 1928.44
Permanent Ineff=
       F       F
Bank Sta=400.94,415.1
XS Rating Curve= 0 ,0
Exp/Cntr=0.3,0.1

Type RM Length L Ch R = 1 ,4092    ,162.2,160.2,158.3
XS GIS Cut Line= 2
     2442925.179      586487.961     2442696.737      587274.538
#Sta/Elev= 30
       0 1970.99   41.561961.283    99.4 1949.05  144.971943.028   170.2 1940.08
   208.5 1933.76   220.2 1930.47   228.5 1926.01     231 1925.61   253.5 1925.97
  273.061924.403   334.3 1924.35   386.8 1927.29     391  1926.6   400.1 1918.77
   403.5 1917.82   408.6 1917.69     416 1918.43   420.1 1920.77   445.1 1945.02
   457.6  1955.7   478.4 1969.99   490.9 1977.26   537.7 2001.91   583.9 2028.06
   636.7 2060.66     670 2080.41   786.2 2142.66     795 2148.17   819.1 2161.33
#Mann= 6 ,-1 , 0
       0      .1       0   41.56      .1       0  144.97     .06       0
  273.06      .1       0   400.1    .045       0     416      .1       0
#XS Ineff= 3 ,-1
       0  182.62 1925.03  182.62  247.57 1936.83  247.57  385.321923.572
Permanent Ineff=
       F       F       F
Bank Sta=400.1,416
XS Rating Curve= 0 ,0
Exp/Cntr=0.3,0.1

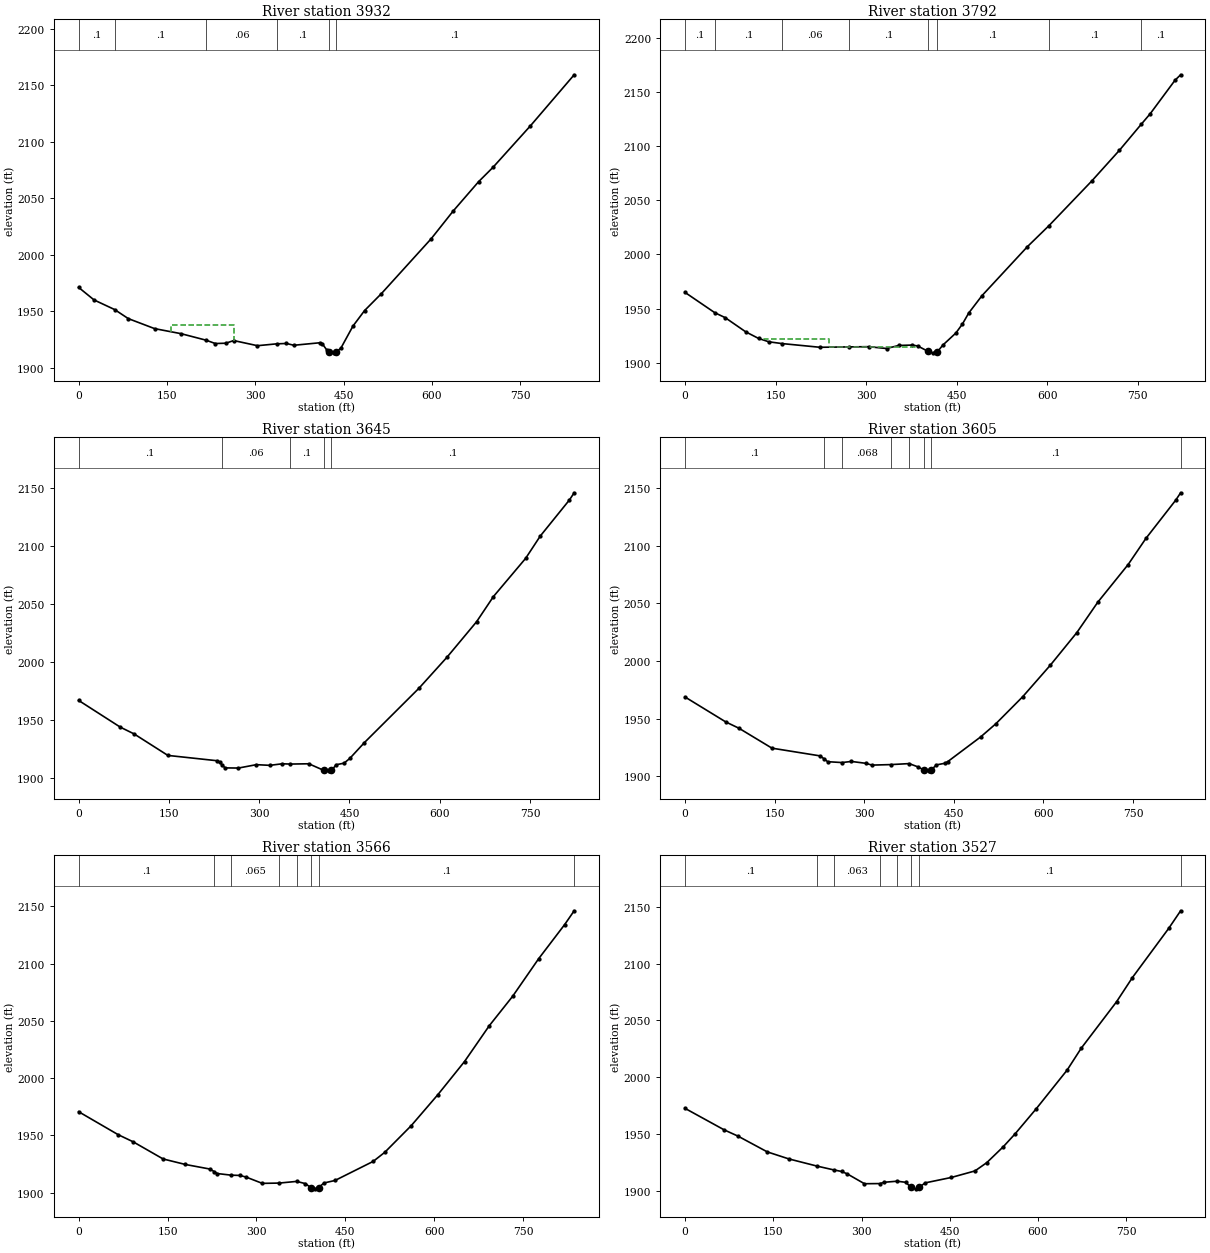
Type RM Length L Ch R = 1 ,3932    ,137.2,139.9,142.3
XS GIS Cut Line= 3
2442837.61832106586456.131861963 2442659.7366896586810.458159429
     2442610.766      587252.561
#Sta/Elev= 30
       0 1970.99    26.1 1959.92   61.12 1951.38    84.3 1943.38     129 1934.51
   173.8 1930.05  216.461924.264     232 1921.32   249.9 1921.59   263.3 1923.95
   303.6  1919.4  336.24 1921.04   352.8 1921.37   365.4 1919.78   409.5    1922
   413.5 1921.25   421.6 1915.39   425.6 1913.71   433.7 1913.08   437.7 1913.61
   445.8 1917.76   465.8 1936.82   485.5 1950.51   514.1 1965.53   598.6 2014.09
   635.8 2038.53   679.1 2064.59   703.3 2077.16   767.1 2114.03   841.3 2159.17
#Mann= 6 ,-1 , 0
       0      .1       0   61.12      .1       0  216.46     .06       0
  336.24      .1       0   425.6    .045       0   437.7      .1       0
#XS Ineff= 3 ,-1
       0  156.58 1920.67  156.58  263.04  1937.6  263.04  406.981919.415
Permanent Ineff=
       F       F       F
Bank Sta=425.6,437.7
XS Rating Curve= 0 ,0
Exp/Cntr=0.3,0.1

Type RM Length L Ch R = 1 ,3792    ,143.4,147,149.3
XS GIS Cut Line= 2
     2442659.055      586420.807     2442386.263      587194.911
#Sta/Elev= 30
       0 1964.89   49.381946.134    66.4 1941.65   100.3 1928.58   121.6 1922.48
   138.5 1919.37  160.091917.731   223.3 1914.28   270.81914.628   303.9 1914.84
   333.6 1913.14   353.8 1915.96     376 1916.31   385.2 1915.51   402.6 1910.46
   409.9 1909.15   417.6 1909.92   426.9 1916.28   448.5 1927.45   459.4 1935.78
   469.8 1945.91   491.8 1961.97     567 2007.18  602.932026.696   673.7 2067.87
   719.5 2096.21  755.242119.977   770.4  2129.9   811.6 2160.91   820.8 2165.87
#Mann= 8 ,-1 , 0
       0      .1       0   49.38      .1       0  160.09     .06       0
   270.8      .1       0   402.6    .045       0   417.6      .1       0
  602.93      .1       0  755.24      .1       0
#XS Ineff= 3 ,-1
       0  131.15 1915.71  131.15  238.37 1922.32  238.69  383.38 1914.95
Permanent Ineff=
       F       F       F
Bank Sta=402.6,417.6
XS Rating Curve= 0 ,0
Exp/Cntr=0.3,0.1

Type RM Length L Ch R = 1 ,3645    ,39.6,40.1,40.1
XS GIS Cut Line= 3
2442551.71350239586374.208038514 2442409.2184366586721.746513634
     2442153.923      587089.569
#Sta/Elev= 30
       0 1966.74    69.4 1943.64    92.1 1937.88   148.3 1919.32   230.5 1914.72
   234.8 1913.42  237.791911.366   243.4 1908.57   265.6 1908.44   295.3 1911.35
   317.8 1910.77   338.5 1912.12  351.721911.866   382.5 1912.12   407.6 1906.38
   415.7 1906.03   419.1 1906.41   421.5 1907.05   427.7 1911.27     441 1912.65
   450.6 1916.75     475 1930.46   565.7 1977.34   612.1 2003.99   661.2 2034.54
   689.2 2056.25   742.8 2089.24   767.1 2108.46   815.5 2139.54   823.4 2145.74
#Mann= 5 ,-1 , 0
       0      .1       0  237.79     .06       0  351.72      .1       0
   407.6    .045       0   419.1      .1       0
#XS Ineff= 2 , 0
          381.85  1911.4
Permanent Ineff=
       F       F
Bank Sta=407.6,419.1
XS Rating Curve= 0 ,0
Exp/Cntr=0.3,0.1

Type RM Length L Ch R = 1 ,3605    ,39,39.4,39.4
XS GIS Cut Line= 5
2442508.28593456586349.8419638722442391.19916674586671.363750507
2442375.34931173586702.8704513632442349.75241769586738.090024122
2442149.94322793587088.097787321
#Sta/Elev= 30
       0 1968.73   68.07 1947.14   90.34 1941.62  145.46 1924.37  226.09 1917.67
  233.24 1914.92  238.74 1912.64  262.67 1911.89  278.57 1912.85   302.4 1911.24
  313.02 1909.67  344.99 1910.13  375.25 1910.98  390.35 1908.06   399.8 1905.38
  408.38  1904.7  411.98 1905.42  420.86 1909.87  434.61 1911.22  439.57  1912.6
  494.97 1934.14  520.24 1945.48  565.35    1969  611.44 1996.25  655.99 2024.63
  691.12 2051.04  741.87 2083.65  771.68 2106.36  821.66 2139.59  829.83 2145.95
#Mann= 8 ,-1 , 0
       0      .1       0  233.24    .061       0  262.67    .068       0
  344.99    .097       0  375.25    .077       0   399.8    .045       0
  411.98      .1       0  829.83      .1       0
#XS Ineff= 2 , 0
          373.681910.403
Permanent Ineff=
       F       F
Bank Sta=399.8,411.98
XS Rating Curve= 0 ,0
Exp/Cntr=0.3,0.1

Type RM Length L Ch R = 1 ,3566    ,39,39.1,39.1
XS GIS Cut Line= 5
2442464.85836674586325.4758892312442359.78752451586653.644326602
2442341.48018687586683.9943890912442314.93627471586718.918686497
2442145.96345586587086.626574642
#Sta/Elev= 30
       0 1970.71   66.74 1950.64   91.96 1944.44  142.57 1929.44  180.04 1924.65
  221.31 1920.66  228.69 1918.47  234.08 1916.71  257.55 1915.29   271.5 1915.08
  281.98 1913.76  309.93 1908.14  338.26 1908.39  367.93 1909.85  382.73 1907.91
     392 1904.37   399.7 1903.36  404.85 1904.43  414.03 1908.47  432.61 1910.66
  497.15 1927.34  516.63 1935.26  561.28 1958.53   606.2 1985.57  651.18  2014.5
  693.05 2045.84  732.38 2071.46  776.22 2104.24  820.16 2134.08  836.25 2146.15
#Mann= 8 ,-1 , 0
       0      .1       0  228.69    .062       0  257.55    .065       0
  338.26    .095       0  367.93    .085       0     392    .045       0
  404.85      .1       0  836.25      .1       0
#XS Ineff= 2 , 0
          365.511909.405
Permanent Ineff=
       F       F
Bank Sta=392,404.85
XS Rating Curve= 0 ,0
Exp/Cntr=0.3,0.1

Type RM Length L Ch R = 1 ,3527    ,37.9,38.6,38.7
XS GIS Cut Line= 5
 2442421.4307947586301.1098122222442328.37587923586635.924900975
2442307.61105871586665.1183249872442280.12012835 586699.74734701
 2442141.9836834 587085.15536182
#Sta/Elev= 30
       0  1972.7   66.45 1953.84   90.13 1948.29  139.79 1934.48  176.45 1928.31
  224.14 1922.03  252.42  1918.7  266.09 1917.29   275.6  1915.2  304.99 1906.51
  331.53 1906.65  338.57  1907.8  360.61 1908.72  375.12 1907.76   384.2 1903.36
  391.93 1902.02  397.73 1903.44  408.69  1907.3  452.75 1912.02  492.93 1917.76
  513.01 1925.03  541.16 1939.06  561.05 1950.27  597.35 1972.54  649.56 2006.31
  673.62 2025.59  733.61 2066.34  760.67 2087.68   822.3 2130.83  842.67 2146.35
#Mann= 8 ,-1 , 0
       0      .1       0  224.14    .063       0  252.42    .063       0
  331.53    .092       0  360.61    .092       0   384.2    .045       0
  397.73      .1       0  842.67      .1       0
#XS Ineff= 2 , 0
          357.341908.407
Permanent Ineff=
       F       F
Bank Sta=384.2,397.73
XS Rating Curve= 0 ,0
Exp/Cntr=0.3,0.1

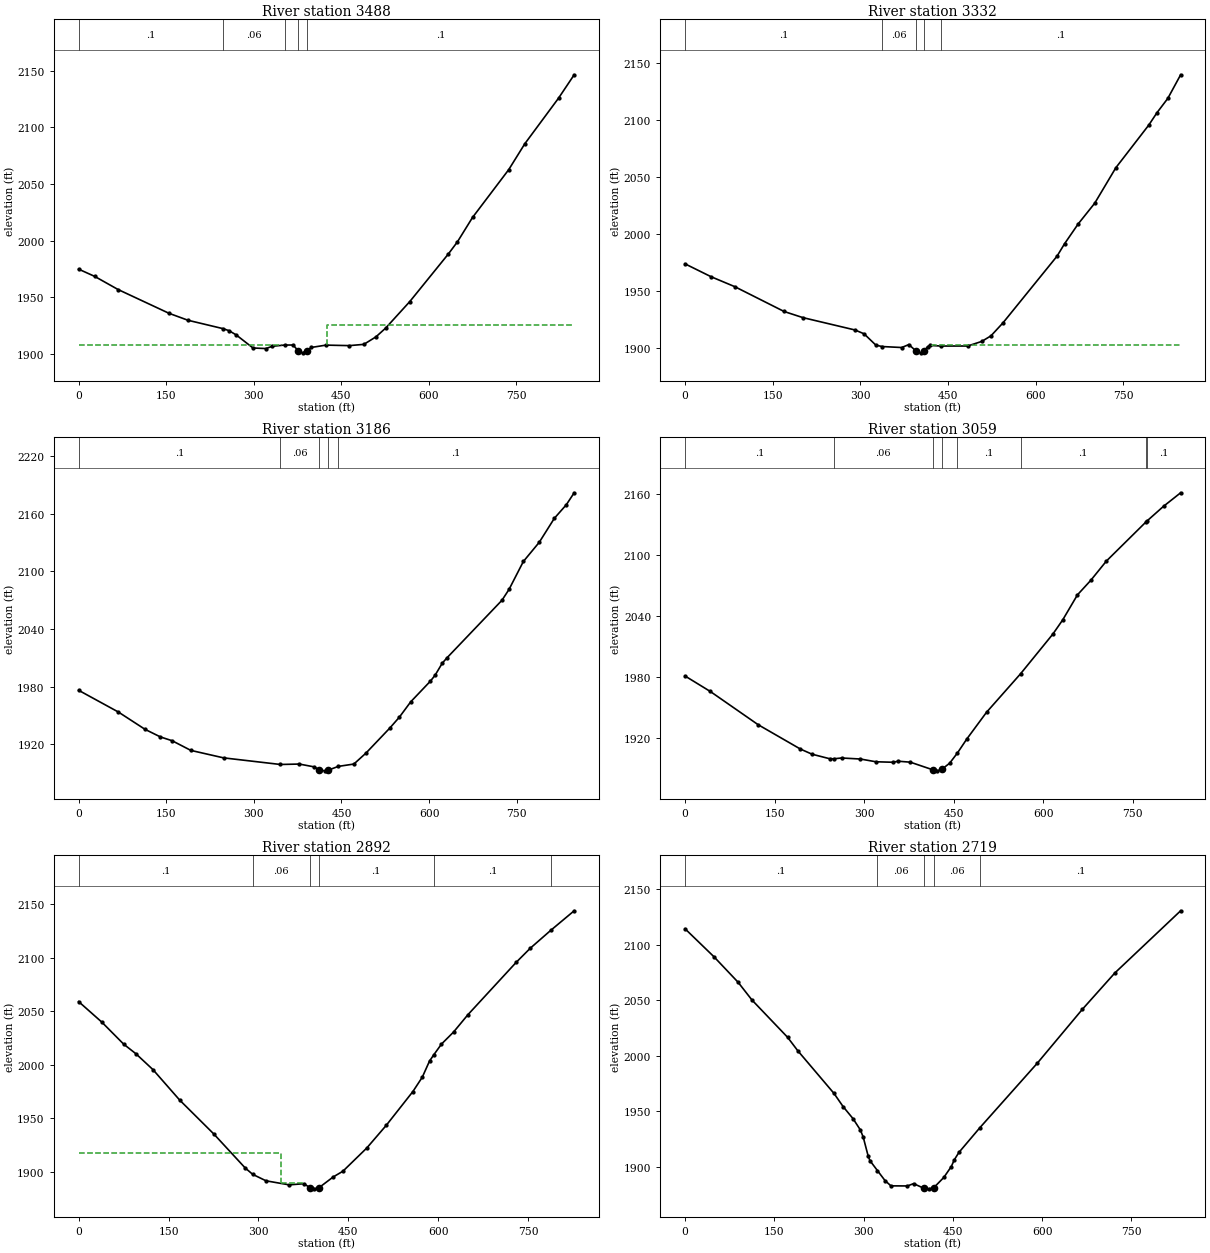
Type RM Length L Ch R = 1 ,3488    ,162.4,156.2,148.6
XS GIS Cut Line= 4
2442378.00323109586276.7437399472442296.96424005586618.205478791
2442245.30398875586680.5760112472442138.00391172587083.684149284
#Sta/Elev= 30
       0 1974.69    27.5 1968.29    67.6 1956.67   154.9 1935.64   187.4 1929.49
   247.31922.105   257.7 1920.29     270 1916.54   298.8 1904.98   320.9 1904.47
   331.7 1906.49  353.291907.591   367.5 1907.61   376.4 1902.36   383.7 1900.69
   390.6 1902.45   398.9 1905.48   423.9 1907.52   463.9 1907.07   488.7 1908.19
   509.4 1914.81   525.9 1922.48   567.4    1946   633.6 1988.17   649.1 1998.86
   674.9 2020.37     737 2062.71   764.6 2085.63   822.4 2125.95   849.1 2146.56
#Mann= 5 ,-1 , 0
       0      .1       0   247.3     .06       0  353.29      .1       0
   376.4    .045       0   390.6      .1       0
#XS Ineff= 2 , 0
          349.17 1907.41  426.27         1925.06
Permanent Ineff=
       F       F
Bank Sta=376.4,390.6
XS Rating Curve= 0 ,0
Exp/Cntr=0.3,0.1

Type RM Length L Ch R = 1 ,3332    ,151.7,146.1,141.3
XS GIS Cut Line= 2
     2442176.168       586211.19     2442075.555       587053.53
#Sta/Elev= 30
       0 1973.66    44.6 1962.36    84.9 1953.69   169.5 1931.85   201.7 1926.47
   291.1 1915.59   306.4 1912.24   326.6 1902.31  337.251901.086   370.9 1900.22
     383 1902.81   396.11896.827   403.1 1895.55   408.4 1896.79   415.2 1900.97
   419.2 1902.06  438.531901.511   483.7 1901.55   507.8 1905.57   523.6 1910.48
   544.1 1921.83   636.7 1980.43   649.5 1991.27     673 2008.81   701.2 2026.92
   737.4  2058.1   793.8 2095.57   807.8 2106.41   826.3 2118.95   848.3 2139.71
#Mann= 5 ,-1 , 0
       0      .1       0  337.25     .06       0   396.1    .045       0
   408.4     .06       0  438.53      .1       0
#XS Ineff= 2 , 0
          381.51  1902.2  423.18          1902.3
Permanent Ineff=
       F       F
Bank Sta=396.1,408.4
XS Rating Curve= 0 ,0
Exp/Cntr=0.3,0.1

Type RM Length L Ch R = 1 ,3186    ,119.7,126.9,134.3
XS GIS Cut Line= 4
2441959.09106101586227.3954751192441964.28351443586573.067892902
2442008.10609952586697.3216854122441932.86625358587060.590287321
#Sta/Elev= 30
       0 1976.04    68.1 1953.37   113.7 1935.35   140.1 1927.42   160.1 1923.47
   192.1 1913.41   248.1 1905.63   345.41898.734   377.9 1899.17   403.4 1896.21
   411.9 1893.13   421.4  1892.1   427.6 1892.89  444.621896.743   471.2 1899.17
   491.9 1910.57   532.7 1936.65   549.1 1948.03   568.6 1964.06   602.2 1985.54
   610.3 1991.77   622.6 2004.32   630.7 2009.92   724.7 2069.83   736.9 2081.21
   761.4 2110.28   788.6 2130.29   814.5 2155.32     835 2169.46   848.4  2181.9
#Mann= 5 ,-1 , 0
       0      .1       0   345.4     .06       0   411.9    .045       0
   427.6     .06       0  444.62      .1       0
Bank Sta=411.9,427.6
XS Rating Curve= 0 ,0
Exp/Cntr=0.3,0.1

Type RM Length L Ch R = 1 ,3059    ,167.2,166.8,166.2
XS GIS Cut Line= 3
2441895.42691172586237.2982873212441901.14563565586508.068430132
     2441767.997      587051.245
#Sta/Elev= 30
       0 1981.21    42.2 1966.03   122.2 1933.39   193.1 1909.39   212.7 1904.29
   242.2 1899.85  248.931899.776   262.2 1900.58   293.6 1899.57   319.6 1896.87
   348.4 1896.38   356.7 1897.41   377.3 1896.46   414.8    1889   422.6 1887.94
   429.71889.327   443.1 1895.42  456.211905.516     472 1919.34   504.9 1945.52
  561.861983.358   616.1 2022.52   632.6 2036.48   657.3 2061.11   679.4 2075.24
   705.8 2094.37  771.74 2132.62  773.152133.421   801.4 2148.16   830.1 2161.49
#Mann= 8 ,-1 , 0
       0      .1       0  248.93     .06       0   414.8    .045       0
   429.7     .06       0  456.21      .1       0  561.86      .1       0
  771.74      .1       0  773.15      .1       0
Bank Sta=414.8,429.7
XS Rating Curve= 0 ,0
Exp/Cntr=0.3,0.1

Type RM Length L Ch R = 1 ,2892    ,179.4,173.2,166.2
XS GIS Cut Line= 4
2441673.29429209586225.3170497612441723.54972302586517.899732371
2441695.28242536586659.215348329      2441720.08      587044.361
#Sta/Elev= 30
       0 2059.04    38.7 2039.85    75.2 2019.24    95.5 2010.32   124.1 1995.41
   168.6 1966.98   225.4 1935.37   278.1 1903.41   290.51897.519   312.7 1891.48
   351.5  1887.7   375.9 1888.78   385.6 1885.22   392.3 1883.98   400.31884.719
   424.9 1895.13     441 1900.45   480.7 1922.08   513.3 1943.33   557.8 1974.98
   573.5 1988.42   585.5 2003.43  592.512009.199   605.5 2019.34   625.6 2030.56
   649.6  2046.8   730.3 2095.84   753.8 2109.03  788.362125.921   826.9 2143.96
#Mann= 6 ,-1 , 0
       0      .1       0   290.5     .06       0   385.6    .045       0
   400.3      .1       0  592.51      .1       0  788.36      .1       0
#XS Ineff= 2 ,-1
       0  338.09 1917.79  338.32  375.86 1889.03
Permanent Ineff=
       F       F
Bank Sta=385.6,400.3
XS Rating Curve= 0 ,0
Exp/Cntr=0.3,0.1

Type RM Length L Ch R = 1 ,2719    ,106.3,107.2,105.6
XS GIS Cut Line= 2
     2441406.672       586264.47     2441677.573      587051.796
#Sta/Elev= 30
       0 2114.45    48.6 2089.21      89  2066.3   112.4 2050.23   172.2 2016.64
   189.3 2004.52   250.2 1966.01   265.4  1954.2   282.2 1943.23   294.5 1933.06
   299.3 1926.59   307.5 1909.71   310.6 1905.37  323.231896.393   335.8 1887.48
   345.8 1882.65   373.6 1882.57   383.9 1884.66   401.9 1880.29   409.2 1879.96
   417.4 1880.76   434.6 1890.19   447.3 1900.07   452.2 1906.05     460 1912.75
  495.521935.248     592 1993.42   667.2  2041.7   722.2 2074.73   832.6 2130.73
#Mann= 5 ,-1 , 0
       0      .1       0  323.23     .06       0   401.9    .045       0
   417.4     .06       0  495.52      .1       0
#XS Ineff= 2 , 0
          383.39 1884.02
Permanent Ineff=
       F       F
Bank Sta=401.9,417.4
XS Rating Curve= 0 ,0
Exp/Cntr=0.3,0.1

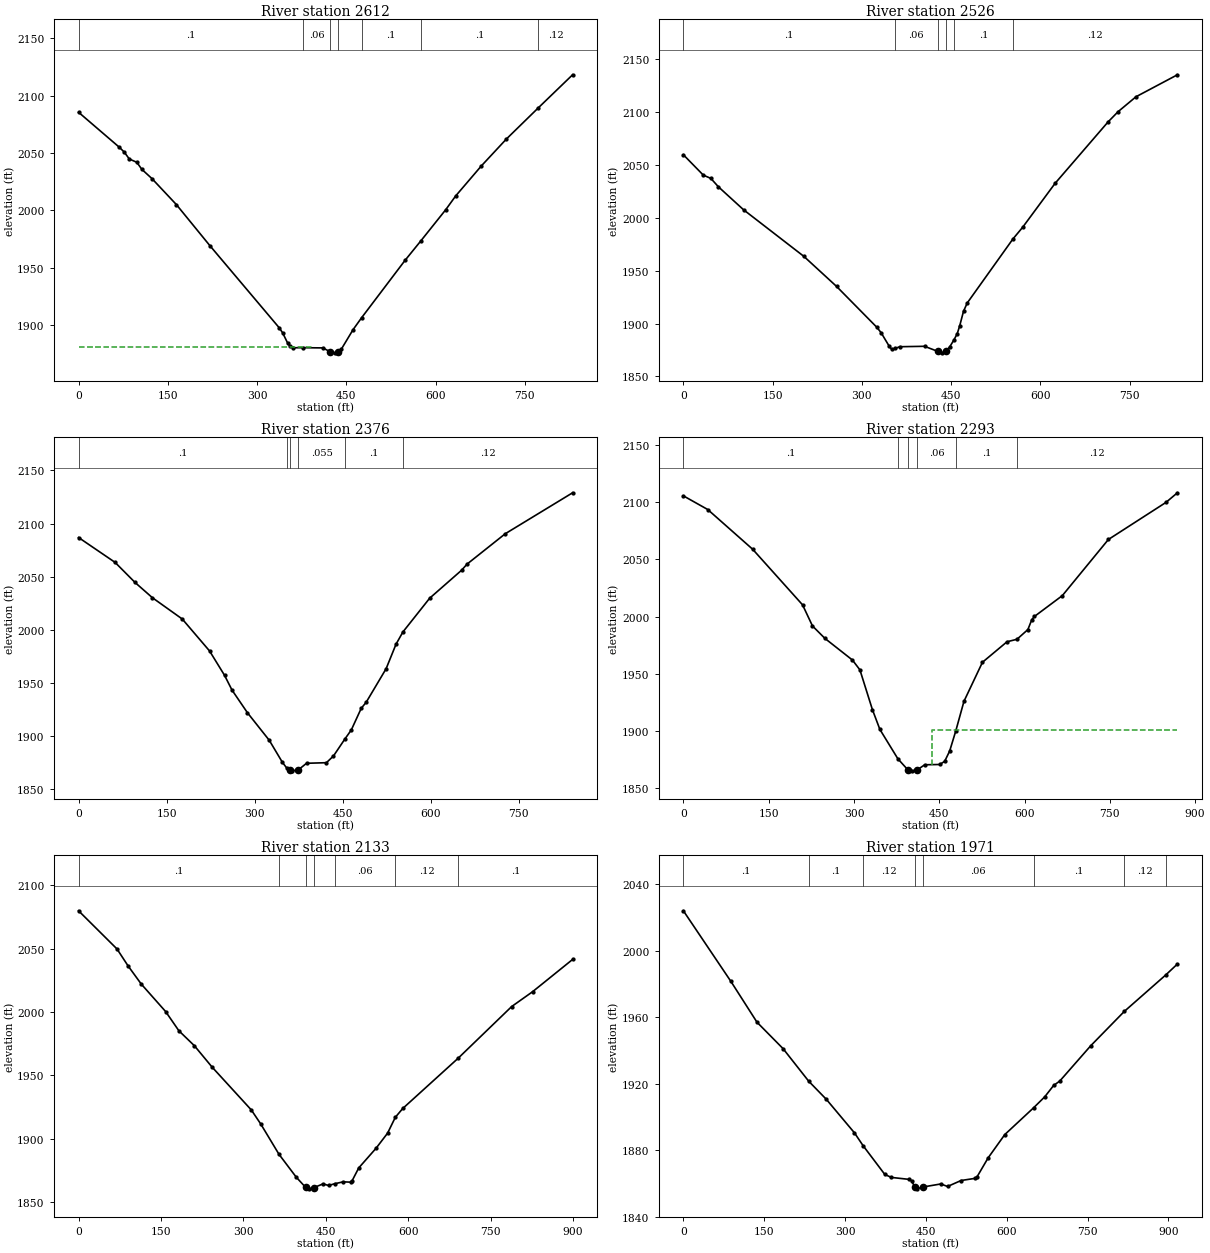
Type RM Length L Ch R = 1 ,2612    ,85.6,85.4,85.9
XS GIS Cut Line= 2
2441310.69180095586298.7710497612441578.70170143587084.640812202
#Sta/Elev= 30
       0  2085.5    68.4 2055.07    76.8  2050.8    85.3 2044.78    97.9 2041.92
   106.4 2035.75   123.3 2027.74   164.3 2005.13   220.5 1969.42   337.6 1897.51
     343  1893.3   351.5 1884.33   355.7 1881.49   359.9  1880.3  376.79 1880.39
   410.6 1880.21   423.3 1876.73   431.8 1875.91     436 1876.25   441.6 1879.08
   461.3 1896.07  475.831906.591   548.7 1956.48  574.861973.196   617.1 2000.62
   633.8  2012.6   676.9 2038.73   719.1 2062.23  772.93 2089.48   830.3 2118.16
#Mann= 7 ,-1 , 0
       0      .1       0  376.79     .06       0   423.3    .045       0
     436     .06       0  475.83      .1       0  574.86      .1       0
  772.93     .12       0
#XS Ineff= 2 , 0
          391.22 1881.21
Permanent Ineff=
       F       F
Bank Sta=423.3,436
XS Rating Curve= 0 ,0
Exp/Cntr(USF)=0,0
Exp/Cntr=0.3,0.1

Type RM Length L Ch R = 1 ,2526    ,150.1,150.7,150.2
XS GIS Cut Line= 2
2441232.50369886586331.7838039812441500.51359933587117.653566422
#Sta/Elev= 30
       0 2059.77    33.5  2040.5    46.2 2037.39    58.8 2029.48   101.1 2007.73
   202.5  1963.6   257.4 1935.19   325.1  1896.5   332.2 1891.47   346.2  1878.3
   350.4 1875.49  355.851876.454   363.7 1878.08   405.3 1878.48   427.21873.757
   434.9 1872.29   441.91874.138   447.6 1877.91  454.891884.681   460.3  1890.5
   464.5 1898.05   470.8 1911.61   477.1 1919.51  553.921980.117   570.1 1991.04
   624.7  2032.7   713.8 2090.88   730.7 2100.59   760.7 2114.67   830.3 2135.47
#Mann= 6 ,-1 , 0
       0      .1       0  355.85     .06       0   427.2    .045       0
   441.9     .06       0  454.89      .1       0  553.92     .12       0
#XS Ineff= 2 , 0
          401.02 1877.44
Permanent Ineff=
       F       F
Bank Sta=427.2,441.9
XS Rating Curve= 0 ,0
Exp/Cntr(USF)=0,0
Exp/Cntr=0.3,0.1

Type RM Length L Ch R = 1 ,2376    ,83.8,82.4,81.5
XS GIS Cut Line= 3
2441110.87776226586352.6339645412441295.77459785586883.170666461
2441463.03119815587107.538905949
#Sta/Elev= 30
       0 2086.85    62.3 2063.38    96.2 2044.51   125.8 2030.12   176.7 2010.04
   223.2 1979.94   248.7 1957.01   261.4 1943.13   287.8 1921.68   324.9 1895.78
   347.4 1874.91  354.321869.922   360.21867.504     363 1866.99   374.61867.974
   388.4 1874.11   422.3 1874.66   434.3    1881  453.471896.755   464.7 1905.53
   481.6  1925.9   490.1 1931.66     524 1963.23   540.9 1986.35  552.621997.854
   598.2 2029.66   652.6 2056.03   661.9 2061.79     727 2090.41   841.7    2129
#Mann= 6 ,-1 , 0
       0      .1       0  354.32     .06       0   360.2    .045       0
   374.6    .055       0  453.47      .1       0  552.62     .12       0
Bank Sta=360.2,374.6
XS Rating Curve= 0 ,0
Exp/Cntr=0.3,0.1

Type RM Length L Ch R = 1 ,2293    ,160.4,160.3,159.3
XS GIS Cut Line= 3
      2440987.51      586356.3112441180.41419905586784.933685411
2441402.62619427587116.173513634
#Sta/Elev= 30
       0 2105.45    42.9 2093.49   121.9 2058.79   209.6 2010.25   227.1 1991.77
   249.1 1980.86   297.3 1962.04   310.5 1953.45   332.4 1918.81   345.6 1901.43
  377.371875.681   394.9 1866.08   402.6 1865.24   411.4 1866.13   424.5 1870.54
   450.8 1870.78   459.6 1873.56   468.4 1882.62  479.071900.047   493.5 1925.99
     526 1960.07   569.3 1978.02  586.711980.145   605.9 1988.64   612.7 1997.13
   617.5 2000.12   666.5 2018.29   747.5 2067.33   848.7  2099.7   868.9 2108.13
#Mann= 6 ,-1 , 0
       0      .1       0  377.37     .06       0   394.9    .045       0
   411.4     .06       0  479.07      .1       0  586.71     .12       0
#XS Ineff= 2 , 0
                           438.1         1900.81
Permanent Ineff=
       F       F
Bank Sta=394.9,411.4
XS Rating Curve= 0 ,0
Exp/Cntr=0.3,0.1

Type RM Length L Ch R = 1 ,2133    ,159.6,162.2,163.9
XS GIS Cut Line= 4
2440948.09539809586361.8583258352440989.64601172586750.274711577
2441040.82296149586849.9400722552441297.69922154587151.833425358
#Sta/Elev= 30
       0 2079.97      70 2049.81    90.1 2036.47   114.2 2022.08   158.5 2000.42
   182.6 1985.25   210.8 1973.46     243  1956.6   314.4 1922.77   331.5 1911.73
   364.81887.743   396.4 1869.59   413.11861.731   418.9  1860.5   428.2 1861.47
   445.1 1864.43   454.9 1863.14   466.21864.532   481.8 1866.03   495.3 1865.77
   497.6 1866.67   509.9 1877.01   541.4 1892.52   562.4 1904.45   576.51916.978
     590 1923.92  690.971963.646   788.2 2004.37   826.2 2016.06   899.1 2041.55
#Mann= 7 ,-1 , 0
       0      .1       0   364.8     .12       0   413.1    .045       0
   428.2     .12       0   466.2     .06       0   576.5     .12       0
  690.97      .1       0
Bank Sta=413.1,428.2
XS Rating Curve= 0 ,0
Exp/Cntr=0.3,0.1

Type RM Length L Ch R = 1 ,1971    ,150.3,152.8,155
XS GIS Cut Line= 4
2440901.33370791586411.5715633952440861.29698875586801.016938992
2440907.72965214586952.557966857  2441171.889167587206.860651671
#Sta/Elev= 30
       0 2024.15    88.3 1981.56   136.6 1957.04     185 1941.12  232.52 1921.53
   265.3 1910.59   317.5 1890.39  333.351882.736   373.8 1865.35   385.9 1863.57
   419.1 1862.38   423.3 1861.55   429.71857.677   432.8 1856.69   444.2 1857.78
   477.7 1859.63   490.2 1858.11   515.3 1861.71   541.7 1863.02   544.6 1863.75
   565.6  1875.4   596.4 1889.37  649.841905.499   670.5  1912.1   687.1 1918.98
   698.3 1921.56   755.9 1942.88  818.181963.549  894.921985.458   916.7 1992.08
#Mann= 8 ,-1 , 0
       0      .1       0  232.52      .1       0  333.35     .12       0
   429.7    .045       0   444.2     .06       0  649.84      .1       0
  818.18     .12       0  894.92      .1       0
Bank Sta=429.7,444.2
XS Rating Curve= 0 ,0
Exp/Cntr=0.3,0.1

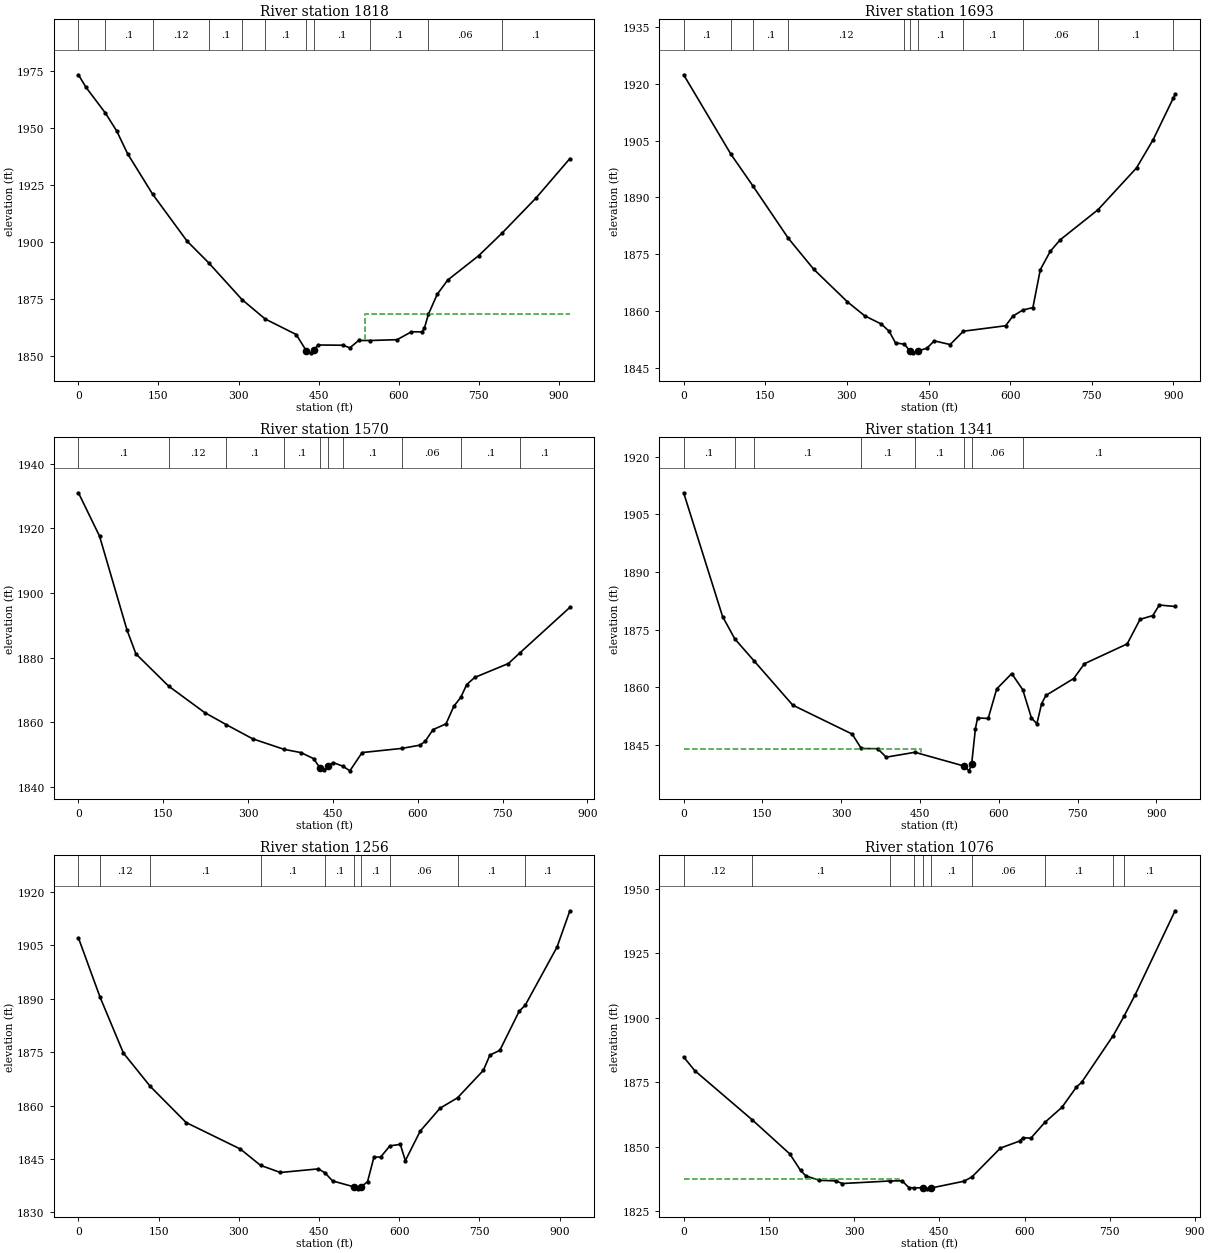
Type RM Length L Ch R = 1 ,1818    ,131.2,125.1,118.9
XS GIS Cut Line= 4
2440804.00254737586425.6906131562440720.49225882586770.335860861
2440746.92595024587023.9712937942441002.59690695587201.243977506
#Sta/Elev= 30
       0 1973.19    14.2  1967.7   50.591956.415    71.8 1948.54    92.1 1938.63
  138.891920.943   203.5 1900.36  244.42 1890.75  306.551874.728  349.951866.235
     408 1859.45     4271852.298   436.1 1851.42   441.61852.561   448.5 1854.86
   495.9 1854.75   508.5 1853.61     525 1856.83   545.61856.823     597 1857.18
   623.8 1860.62   643.7 1860.62   648.1 1862.16  655.681868.294   672.2 1877.06
   691.9  1883.3   749.8 1893.95  793.621903.842   857.4 1919.25   920.7 1936.48
#Mann= 11 ,-1 , 0
       0      .1       0   50.59      .1       0  138.89     .12       0
  244.42      .1       0  306.55     .12       0  349.95      .1       0
     427    .045       0   441.6      .1       0   545.6      .1       0
  655.68     .06       0  793.62      .1       0
#XS Ineff= 2 , 0
                          536.24          1868.3
Permanent Ineff=
       F       F
Bank Sta=427,441.6
XS Rating Curve= 0 ,0
Exp/Cntr=0.3,0.1

Type RM Length L Ch R = 1 ,1693    ,121.3,122.4,123.6
XS GIS Cut Line= 4
2440645.40260361586499.3938394692440565.01835187586822.160496511
 2440728.1710835587058.4679567122440957.30961963587225.102552148
#Sta/Elev= 30
       0 1922.47   86.661901.488  126.711893.167  192.471879.168   239.1 1870.99
   300.9 1862.39   332.6 1858.69   363.4 1856.49   377.8 1854.55   389.3 1851.51
  405.781851.163   415.31849.427   421.6 1848.88   430.11849.391   446.8 1850.07
   460.5 1852.05   489.7 1851.07   514.11854.605   591.7 1856.05   604.9 1858.59
  623.151860.191   641.8 1860.86   655.4  1870.9   673.7 1875.74     692  1878.8
  761.431886.752   832.2 1897.82   862.7 1905.27  899.711916.273   903.1 1917.31
#Mann= 11 ,-1 , 0
       0      .1       0   86.66     .12       0  126.71      .1       0
  192.47     .12       0  405.78      .1       0   415.3    .045       0
   430.1      .1       0   514.1      .1       0  623.15     .06       0
  761.43      .1       0  899.71      .1       0
Bank Sta=415.3,430.1
XS Rating Curve= 0 ,0
Exp/Cntr=0.3,0.1

Type RM Length L Ch R = 1 ,1570    ,219.4,229.3,235.5
XS GIS Cut Line= 3
2440528.95576891586542.5347511932440478.08670498586899.061568766
2440728.55670143587341.969011247
#Sta/Elev= 30
       0    1931    37.3 1917.61    85.8 1888.61   101.7 1881.17  159.591871.207
   223.1 1863.05  261.551859.295     308 1854.93  363.581851.668   393.7 1850.65
   415.7 1848.81   427.71845.811   434.1 1845.28   440.51846.399   450.5 1847.59
  467.81 1846.43     480 1845.02   501.6 1850.67  572.041851.963   604.1 1852.97
   613.2 1854.16     627 1857.76     650 1859.55   663.8 1864.98  676.281867.777
   686.5 1871.67   700.6 1873.89   760.3  1878.2  780.511881.472     869 1895.56
#Mann= 10 ,-1 , 0
       0      .1       0  159.59     .12       0  261.55      .1       0
  363.58      .1       0   427.7    .045       0   440.5      .1       0
  467.81      .1       0  572.04     .06       0  676.28      .1       0
  780.51      .1       0
Bank Sta=427.7,440.5
XS Rating Curve= 0 ,0
Exp/Cntr=0.3,0.1

Type RM Length L Ch R = 1 ,1341    ,80.7,85.2,88.6
XS GIS Cut Line= 3
2440437.16332106586582.1646629182440349.36099707587164.871796778
2440284.10640117587504.894658144
#Sta/Elev= 30
       0 1910.59    74.1  1878.4    97.41872.574   133.7 1866.92   207.6 1855.36
   320.8 1847.82  338.111844.075   369.4 1844.01   385.5 1841.82  440.321843.086
   534.2 1839.49   543.3 1838.26   548.2 1840.02   555.4 1849.24   559.5 1852.03
   579.7 1851.88   595.9 1859.56   624.5 1863.56  645.481859.366   662.1 1851.98
   672.4 1850.52   681.4 1855.74   689.6 1857.88   742.5 1862.27   762.9 1866.12
   844.3 1871.28   868.8 1877.66   893.2 1878.66   905.4 1881.39   935.5 1881.01
#Mann= 8 ,-1 , 0
       0      .1       0    97.4     .12       0   133.7      .1       0
  338.11      .1       0  440.32      .1       0   534.2    .045       0
   548.2     .06       0  645.48      .1       0
#XS Ineff= 2 , 0
          451.43 1844.04
Permanent Ineff=
       F       F
Bank Sta=534.2,548.2
XS Rating Curve= 0 ,0
Exp/Cntr=0.3,0.1

Type RM Length L Ch R = 1 ,1256    ,184.7,180.4,175.9
XS GIS Cut Line= 4
2440419.95501932586584.2659317272440370.23050405586910.070576304
 2440254.9443756587132.2904478522440081.36539809587423.951536127
#Sta/Elev= 30
       0 1907.09   40.431890.442    84.1 1874.75  134.381865.371   201.5 1855.22
     303 1847.77  340.611843.204   377.8 1841.19     449 1842.21  461.551841.047
   475.3 1838.83   515.31837.157   523.1  1836.6     5291837.165   540.9 1838.64
   552.8  1845.5   565.4 1845.54  582.611848.659   602.1  1849.1   611.6 1844.52
   639.4 1852.83   676.6 1859.26  709.161862.165   757.5 1869.88   769.7 1874.16
   788.3  1875.5   824.6 1886.51  835.721888.142   895.4 1904.53   919.3 1914.69
#Mann= 10 ,-1 , 0
       0      .1       0   40.43     .12       0  134.38      .1       0
  340.61      .1       0  461.55      .1       0   515.3    .045       0
     529      .1       0  582.61     .06       0  709.16      .1       0
  835.72      .1       0
#XS Ineff= 2 , 0
          450.91 1841.09
Permanent Ineff=
       F       F
Bank Sta=515.3,529
XS Rating Curve= 0 ,0
Exp/Cntr=0.3,0.1

Type RM Length L Ch R = 1 ,1076    ,165.7,168.1,169.5
XS GIS Cut Line= 4
 2440279.1554366586574.2894751192440177.16946572586763.648811099
2440130.77922631 587129.405144512439964.40613804587355.927187798
#Sta/Elev= 30
       0 1884.73    19.5 1879.43  120.961860.298   186.7 1847.16   205.7 1840.76
   215.1 1838.61     239 1836.91   267.3 1836.69   279.4 1835.67  363.511836.664
   384.2 1836.73   396.3  1834.1  405.741833.988   420.81834.026   428.5 1833.61
   435.2 1833.92     493 1836.55  507.231838.194   557.5 1849.42   591.2 1852.13
   597.5 1853.44     611 1853.25  635.611859.371   665.6 1865.19   691.1 1873.04
   700.4 1874.91  755.98 1893.05  774.85 1900.49   794.6 1908.88   864.8  1941.4
#Mann= 10 ,-1 , 0
       0     .12       0  120.96      .1       0  363.51      .1       0
  405.74      .1       0   420.8    .045       0   435.2      .1       0
  507.23     .06       0  635.61      .1       0  755.98      .1       0
  774.85      .1       0
#XS Ineff= 2 , 0
          379.41 1837.45
Permanent Ineff=
       F       F
Bank Sta=420.8,435.2
XS Rating Curve= 0 ,0
Exp/Cntr=0.3,0.1