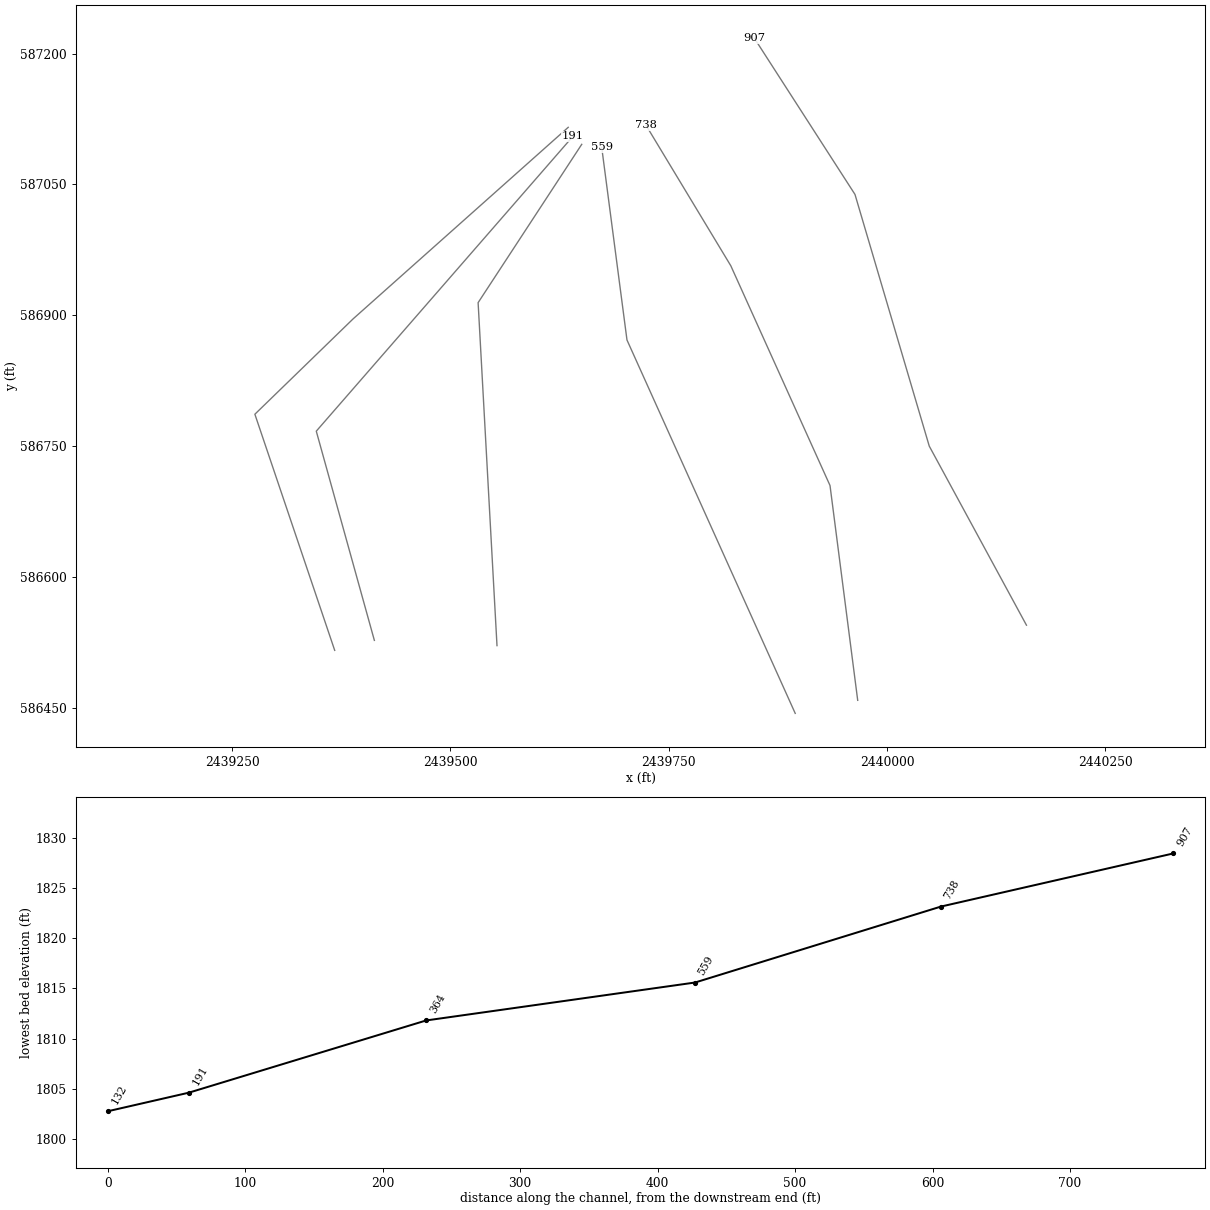
HEC-RAS study DRYRN2.prj: DRYRN2

--- DRYRN2.g01 (geometry) --- (continued)

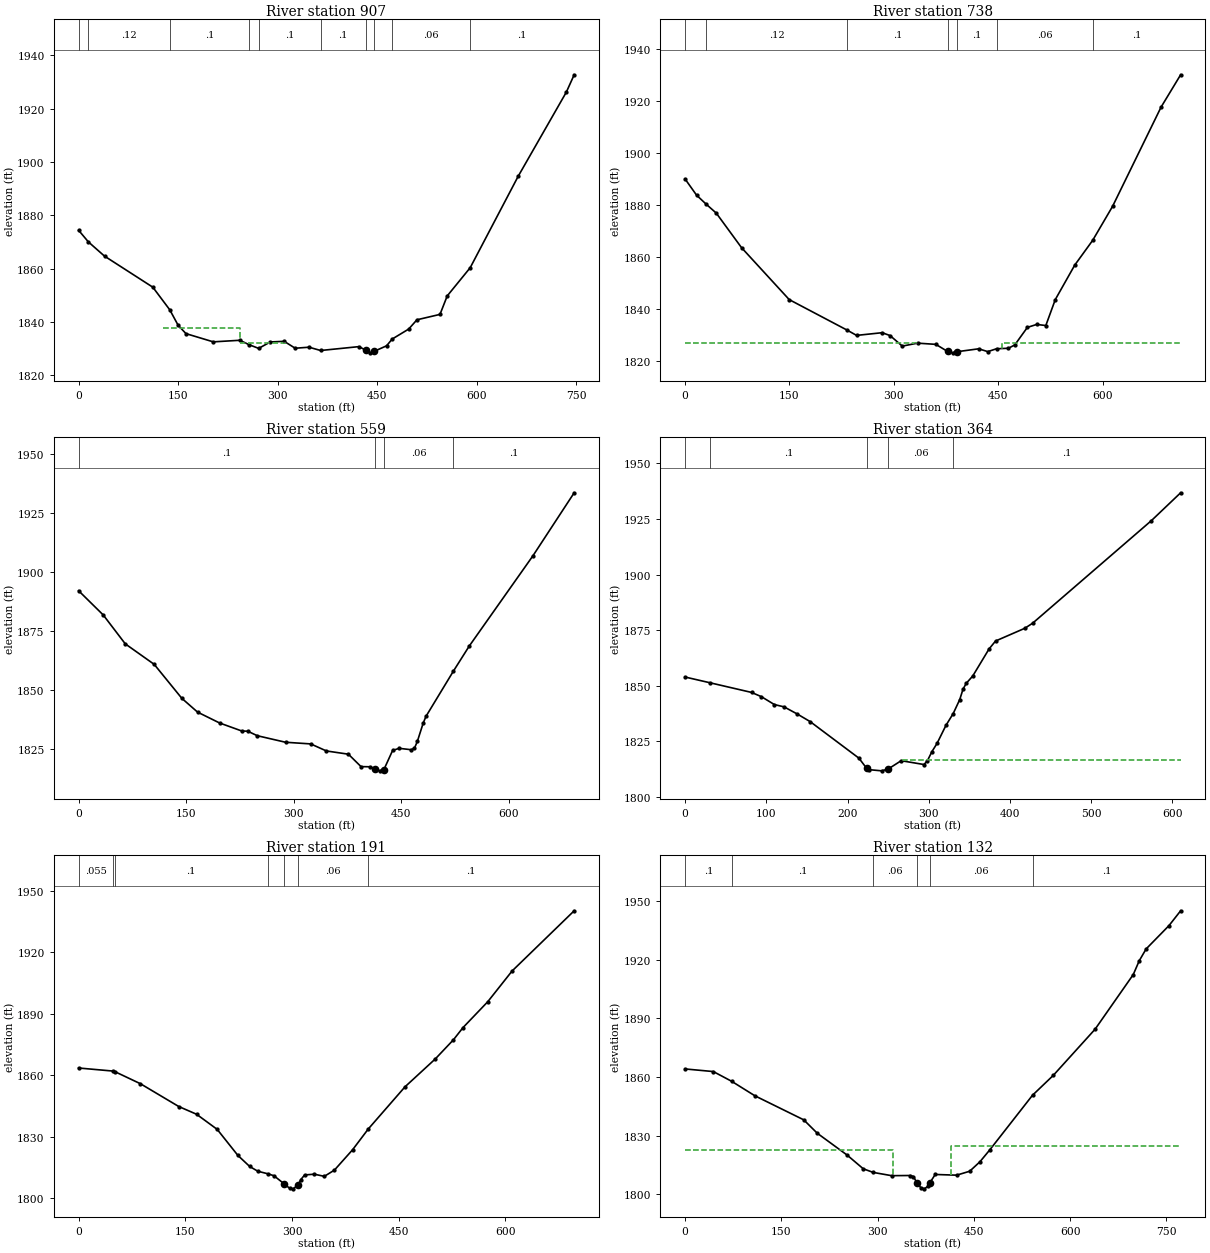
Type RM Length L Ch R = 1 ,907     ,167.5,169.2,170.7
XS GIS Cut Line= 4
2440159.79360191586545.1466131562440048.44375781586750.274711577
2439963.37778971587038.5601717782439848.18868288587217.382158595
#Sta/Elev= 30
       0 1874.43   14.691870.069      39 1864.74   111.8 1853.08  137.341844.597
     150 1838.77   161.8 1835.66   202.9 1832.58   242.9 1833.17  256.781831.521
  271.281830.131   288.8 1832.54   309.7 1832.78   326.3 1830.19   347.2 1830.57
  364.631829.339   422.3 1830.79   432.4 1829.51   438.9 1828.46   445.61829.062
     464 1831.09  472.471833.632   497.3 1837.37   509.8 1840.86   544.5 1842.88
   555.4 1849.81  590.041860.396   662.4 1894.72   734.9 1926.26   746.7 1932.76
#Mann= 10 ,-1 , 0
       0      .1       0   14.69     .12       0  137.34      .1       0
  256.78      .1       0  271.28      .1       0  364.63      .1       0
   432.4    .045       0   445.6      .1       0  472.47     .06       0
  590.04      .1       0
#XS Ineff= 3 ,-1
       0  127.31 1832.21  127.31   242.7 1837.64   242.7  314.22 1832.21
Permanent Ineff=
       F       F       F
Bank Sta=432.4,445.6
XS Rating Curve= 0 ,0
Exp/Cntr=0.3,0.1

Type RM Length L Ch R = 1 ,738     ,177.5,178.9,177.2
XS GIS Cut Line= 4
2439966.48770621586459.0595521482439934.76391187586705.137125688
 2439821.1417287586956.8179839792439724.15799343587117.541467372
#Sta/Elev= 30
       0 1890.03    16.5 1883.81   30.081880.401    44.8 1876.91    81.1 1863.62
   149.6 1843.64  233.181831.844   246.4 1829.87   283.2 1830.91   294.5  1829.8
   312.1 1825.75     334 1826.89   360.3 1826.42   377.21823.682   384.5 1823.16
   390.51823.587   421.8 1824.71   434.9 1823.63  447.451824.731   464.6 1824.92
   473.7 1826.21   491.8 1832.95   505.1 1834.08   518.3 1833.67   531.9 1843.65
   559.9 1856.93  585.541866.406   614.2 1879.51   683.9  1917.7     712 1930.13
#Mann= 7 ,-1 , 0
       0      .1       0   30.08     .12       0  233.18      .1       0
   377.2    .045       0   390.5      .1       0  447.45     .06       0
  585.54      .1       0
#XS Ineff= 2 , 0
          334.74 1827.06  456.01          1827.1
Permanent Ineff=
       F       F
Bank Sta=377.2,390.5
XS Rating Curve= 0 ,0
Exp/Cntr=0.3,0.1

Type RM Length L Ch R = 1 ,559     ,203.7,195.6,191.2
XS GIS Cut Line= 3
 2439894.9172713586444.1187736872439702.18830334 586871.83611077
2439673.26360322587092.392000692
#Sta/Elev= 30
       0 1891.96    34.4 1881.67    65.1 1869.44   105.5 1860.74     144 1846.35
     166 1840.49   196.7 1835.89   227.4 1832.52   236.2 1832.38   249.3 1830.49
   288.8 1827.71   323.9 1827.01   345.8 1824.02   376.5 1822.65   394.1 1817.38
   407.3 1817.31     414 1816.34   420.4 1815.59   426.1 1816.15   438.2 1824.23
   447.3 1825.14   464.3 1824.54   468.7  1825.2   472.7 1828.04   480.8 1835.75
   484.8  1838.7  522.99 1857.85   545.3 1868.57   634.1 1906.81   691.6 1933.51
#Mann= 4 ,-1 , 0
       0      .1       0     414    .045       0   426.1     .06       0
  522.99      .1       0
Bank Sta=414,426.1
XS Rating Curve= 0 ,0
Exp/Cntr=0.3,0.1

Type RM Length L Ch R = 1 ,364     ,188,172.7,162.9
XS GIS Cut Line= 3
2439553.29638466586521.7145095812439531.66468206586914.604827523
2439650.35329278587095.954210311
#Sta/Elev= 30
       0 1853.98   31.08 1851.36    81.8 1847.06    93.9 1845.16   109.9 1841.61
   121.9 1840.56   137.9  1837.4     154 1833.94     214 1817.52   223.61812.934
   226.1 1812.35   242.1 1811.81   250.1 1812.64   266.1 1816.37   294.1 1814.65
   298.2 1816.24     304 1820.48   310.2 1824.12   321.2 1832.24  330.191837.584
   338.2 1843.86   342.2 1848.48   346.2 1851.16   354.2 1854.43   374.3 1866.61
   382.3 1870.17   418.3 1875.89   427.9 1878.16   574.3 1924.32   610.2  1936.8
#Mann= 5 ,-1 , 0
       0    .055       0   31.08      .1       0   223.6    .045       0
   250.1     .06       0  330.19      .1       0
#XS Ineff= 2 , 0
                          267.92         1816.59
Permanent Ineff=
       F       F
Bank Sta=223.6,250.1
XS Rating Curve= 0 ,0
Exp/Cntr(USF)=0,0
Exp/Cntr=0.3,0.1

Type RM Length L Ch R = 1 ,191     ,60.2,58.9,57.7
XS GIS Cut Line= 3
 2439412.8189778586527.7243712052439346.27964483586767.387297961
2439640.32271813587105.187450061
#Sta/Elev= 30
       0  1863.6   48.981862.086   50.521861.893    86.9 1855.92   140.8 1844.79
   165.7 1841.04   194.8 1833.64   223.9 1820.91   240.5 1815.52   251.9  1813.2
  265.84 1811.97   274.6    1811   288.7  1807.1   296.5 1804.92   301.8 1804.61
   308.6 1806.69   312.4 1809.15   317.7 1811.39   331.3 1811.76   345.4 1810.71
   359.6 1813.76   385.1 1823.68  407.161833.835   458.8 1854.42   501.4 1868.04
   526.9 1877.39   540.4 1883.36   575.1 1895.95   609.3 1910.95   696.6 1940.36
#Mann= 7 ,-1 , 0
       0    .055       0   48.98      .1       0   50.52      .1       0
  265.84     .06       0   288.7    .045       0   308.6     .06       0
  407.16      .1       0
#XS Ineff= 2 , 0
                          327.14         1811.01
Permanent Ineff=
       F       F
Bank Sta=288.7,308.6
XS Rating Curve= 0 ,0
Exp/Cntr(USF)=0,0
Exp/Cntr=0.3,0.1

Type RM Length L Ch R = 1 ,132     ,,,
XS GIS Cut Line= 4
2439367.38315816586516.3050625862439275.94187084586786.789654393
2439388.52213371586896.0726487022439634.87528547587115.439165805
#Sta/Elev= 30
       0 1864.16      44 1862.82   72.48 1857.85   108.9 1850.39   184.9  1838.1
     206 1831.23   252.4 1820.08   277.7 1813.02  293.17 1811.17   321.9  1809.5
   350.7 1809.59   355.8 1809.07   361.1 1805.97   367.1 1803.44   372.8 1802.76
   378.3 1804.04   381.3 1805.76   389.8 1810.12   423.2 1809.76   443.5 1811.77
   459.5 1816.62   474.7 1822.65  541.43 1850.69   573.9 1860.89     639 1884.52
   698.5 1912.51   707.8 1919.58   718.5 1925.61   754.2 1937.59   772.3 1945.16
#Mann= 6 ,-1 , 0
       0      .1       0   72.48      .1       0  293.17     .06       0
   361.1    .045       0   381.3     .06       0  541.43      .1       0
#XS Ineff= 2 , 0
          323.48 1822.81  413.89         1824.65
Permanent Ineff=
       F       F
Bank Sta=361.1,381.3
XS Rating Curve= 0 ,0
Exp/Cntr=0.5,0.3
LCMann Table=0

Chan Stop Cuts=-1
Use User Specified Reach Order=0
Composite Channel Slope=5